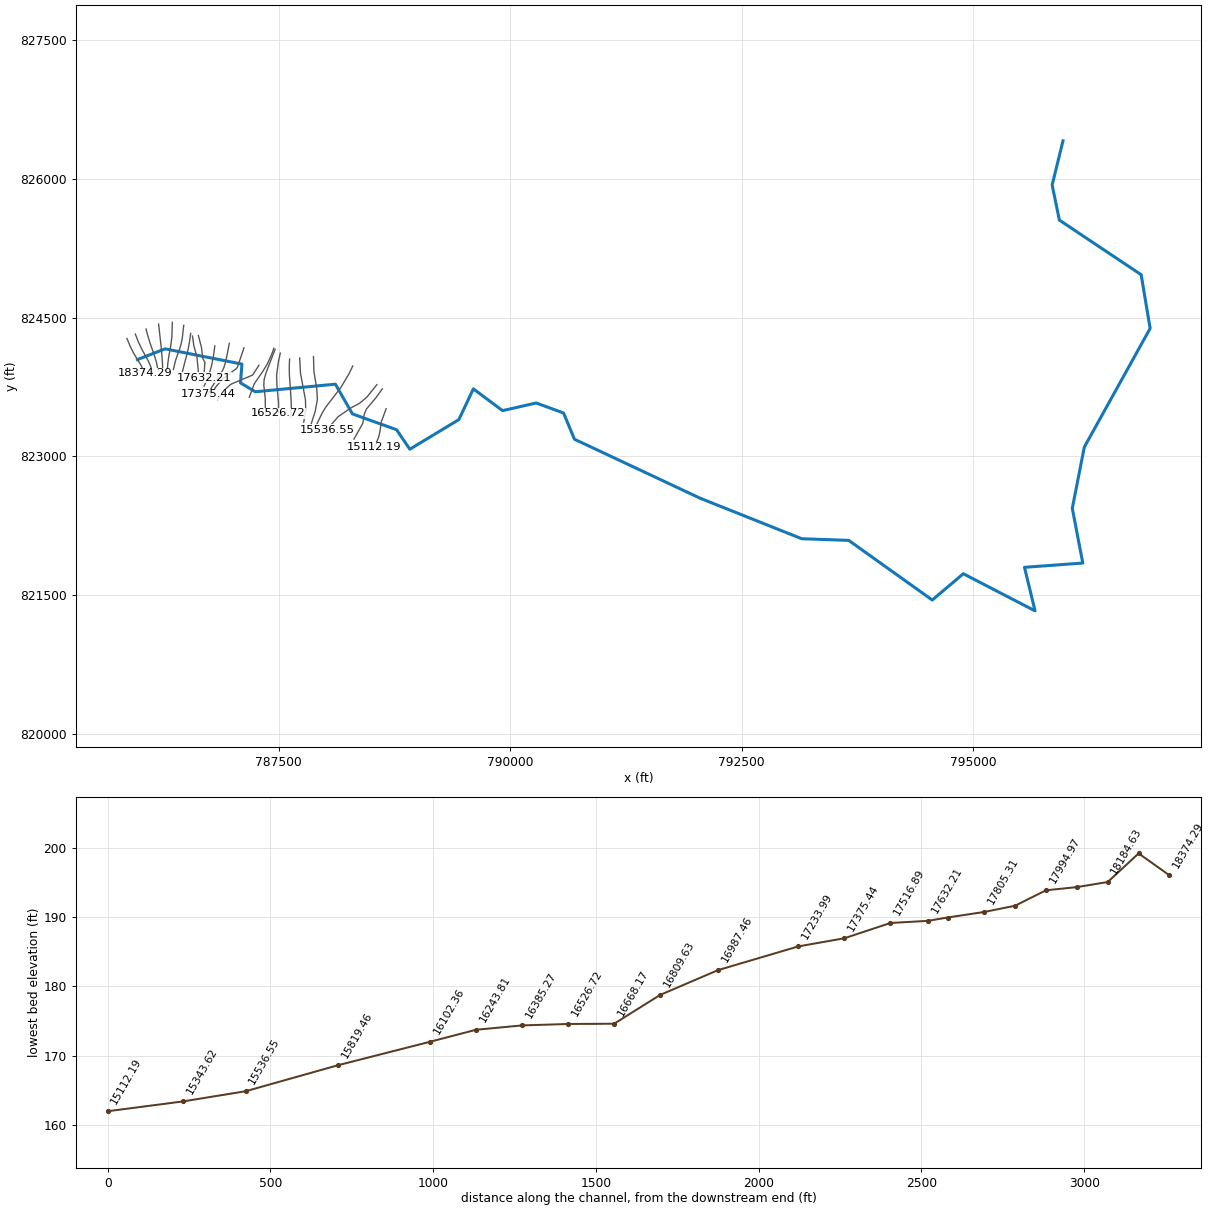
--- 18193_ras.prj (project) ---

Proj Title=18193
Current Plan=p01
Default Exp/Contr=0.3,0.1
English Units
Geom File=g01
Flow File=f01
Plan File=p01
Y Axis Title=Elevation
X Axis Title(PF)=Main Channel Distance
X Axis Title(XS)=Station
BEGIN DESCRIPTION:
RFD model 18193 exported to HEC-RAS
END DESCRIPTION:

--- 18193_ras.p01 (plan) ---

Plan Title=Plan 01
Program Version=4.10
Short Identifier=Plan 01
Geom File=g01
Flow File=f01
Subcritical Flow
Calc Critical at every XS
Secant Critical Depth

--- 18193_ras.f01 (steady flow) ---

Flow Title=Flow 01
Program Version=5.01
Number of Profiles= 6
Profile Names=10yr,25yr,50yr,100yr,100plus,500yr
River Rch & RM=18193,59,18374.29
 2428.32 4031.62 5588.55 7052.2910296.3412659.42
River Rch & RM=18193,59,18184.63
 2430.33 4035.08 5593.48 7058.6210305.5912669.67
River Rch & RM=18193,59, 18089.8
 2442.81 4056.64 5624.14 7098.1610363.3212733.93
River Rch & RM=18193,59,17994.97
 2445.16  4060.7 5629.91 7105.6110374.1912746.02
River Rch & RM=18193,59,17900.14
 2454.47 4076.72 5652.67 7134.9110416.9712793.42
River Rch & RM=18193,59,17805.31
 2455.92 4079.23 5656.22 7139.4910423.6612800.84
River Rch & RM=18193,59,17692.49
 2456.82 4080.79 5658.45 7142.3610427.8412805.48
River Rch & RM=18193,59,17632.21
 2457.91 4082.67 5661.11  7145.810432.8612811.05
River Rch & RM=18193,59,17516.89
 2462.06 4089.84 5671.31 7158.9510452.0612832.39
River Rch & RM=18193,59,17375.44
 2464.05 4093.27 5676.19 7165.2410461.2512842.59
River Rch & RM=18193,59,17233.99
 2464.78 4094.52 5677.97 7167.53 10464.6 12846.3
River Rch & RM=18193,59,16987.46
 2475.83 4113.58 5705.06 7202.4410515.57 12902.8
River Rch & RM=18193,59,16809.63
    2478 4117.33 5710.39  7209.310525.5812913.91
River Rch & RM=18193,59,16668.17
 2482.88 4125.75 5722.36 7224.7310548.1112938.88
River Rch & RM=18193,59,16526.72
 2488.13 4134.79 5735.22 7241.3110572.3112965.68
River Rch & RM=18193,59,16385.27
  2491.9 4141.31  5744.5 7253.2710589.7812985.07
River Rch & RM=18193,59,16243.81
  2495.3 4147.19 5752.87 7264.0810605.5613002.61
River Rch & RM=18193,59,16102.36
 2498.13 4152.11 5759.89 7273.15 10618.813017.37
River Rch & RM=18193,59,15819.46
  2503.8 4161.95 5773.91 7291.2810645.2713046.87
River Rch & RM=18193,59,15536.55
 2507.87 4169.01 5783.98  7304.310664.2813068.05
River Rch & RM=18193,59,15343.62
 2510.53 4173.61 5790.55 7312.7910676.6713081.86
River Rch & RM=18193,59,15112.19
 2513.89 4179.44 5798.87 7323.5410692.3713099.35
River Rch & RM=18193,59,14655.97
 2518.84 4188.03 5811.12 7339.3810715.49 13125.1
River Rch & RM=18193,59,14366.27
 2523.08 4195.39 5821.61 7352.95 10735.313147.16
River Rch & RM=18193,59,   14158
 2527.85 4203.66 5833.41  7368.210757.5713171.95
River Rch & RM=18193,59,13661.24
 2531.55 4210.09 5842.59 7380.0610774.8913191.23
River Rch & RM=18193,59,13420.77
 4500.04 7544.0310529.6113358.5819503.5322158.15
River Rch & RM=18193,59, 13187.3
 4503.63 7550.2610538.51 13370.119520.3422175.36
River Rch & RM=18193,59,12953.83
  4505.5 7553.5110543.1613376.1119529.1222184.34
River Rch & RM=18193,59,12739.27
 4538.09 7609.7910623.2813479.4519679.9922337.48
River Rch & RM=18193,59,12486.89
  4539.8 7612.7710627.5413484.9519688.0222345.69
River Rch & RM=18193,59,12253.42
 4544.16 7620.3310638.3513498.9419708.4522366.57
River Rch & RM=18193,59,11982.67
 4548.01 7627.0410647.9513511.3819726.6122385.21
River Rch & RM=18193,59,11741.94
 4551.09 7632.4210655.6413521.3419741.1622400.12
River Rch & RM=18193,59,11516.61
 4552.64 7635.1110659.4913526.3219748.4322407.57
River Rch & RM=18193,59,11158.28
 4579.95 7682.4910727.15 13613.819876.1522537.82
River Rch & RM=18193,59,10783.71
 4582.53 7687.0110733.6313622.2119888.4322550.45
River Rch & RM=18193,59,10644.98
 4615.42 7744.0610815.0913727.53 20042.222707.07
River Rch & RM=18193,59,10400.21
  5697.5 9619.31 13491.217185.4625090.78 27752.9
River Rch & RM=18193,59,10121.64
 5709.74 9640.5913521.6317224.8625148.2927809.73
River Rch & RM=18193,59,9910.675
 5715.37 9650.4413535.7717243.22 25175.127836.43
River Rch & RM=18193,59,9665.906
  5724.6 9666.5813558.9517273.3225219.05 27880.2
River Rch & RM=18193,59,9421.138
 5727.48 9671.6313566.1917282.7325232.7927893.88
River Rch & RM=18193,59, 9176.37
 5733.39 9681.9713581.0417302.0225260.95 27921.9
River Rch & RM=18193,59,8931.601
 5757.53 9723.9413641.0717379.7325374.41 28033.9
River Rch & RM=18193,59,8592.011
 5763.02 9733.5313654.83 17397.6 25400.528059.83
River Rch & RM=18193,59,8442.064
 5763.31 9734.0413655.5517398.5425401.8728061.19
River Rch & RM=18193,59,8254.437
 5786.83 9775.2913714.8917475.7225514.5628173.65
River Rch & RM=18193,59,7952.527
  5827.1 9845.95 13816.517607.9225707.5628366.12
River Rch & RM=18193,59, 7462.99
  5840.7 9869.75 13850.717652.3625772.4428430.62
River Rch & RM=18193,59,7088.286
 5842.57 9873.0213855.3917658.4625781.3528439.44
River Rch & RM=18193,59,6483.916
 5847.99 9882.5213869.04 17676.225807.2528465.22
River Rch & RM=18193,59,5994.379
  5851.6 9888.8313878.0817687.9325824.3828482.18
River Rch & RM=18193,59,5504.842
 5929.9710026.1214075.3917944.4426198.8828854.19
River Rch & RM=18193,59,4843.207
 5931.1210028.1314078.2817948.1926204.3528859.59
Boundary for River Rch & Prof#=18193,59,1
Up Type= 0
Dn Type= 2
Boundary for River Rch & Prof#=18193,59,2
Up Type= 0
Dn Type= 2
Boundary for River Rch & Prof#=18193,59,2
Up Type= 0
Dn Type= 2
Boundary for River Rch & Prof#=18193,59,2
Up Type= 0
Dn Type= 2
Boundary for River Rch & Prof#=18193,59,2
Up Type= 0
Dn Type= 2
Boundary for River Rch & Prof#=18193,59,2
Up Type= 0
Dn Type= 2

--- 18193_ras.g01 (geometry) ---

Geom Title=18193
Program Version=4.10

River Reach=18193,59
Reach XY= 30
785975.578109681824047.063752638  786274.7738131824163.032111394
787103.850899845823998.209038687787088.006886006823795.125959158
787247.245083841823698.838718263788112.762075486823780.911041921
788296.496071577823459.435667743788773.505905571823287.804383877
788916.277599901823076.812168007789446.280732036 823397.81530424
789602.200890811823730.053168978 789917.49359101823494.664891669
790280.594322949823577.273636142790576.179126413823469.210918004
790694.193578808823185.065888858792053.079821975822545.909471047
 793147.61268285822108.569004613793655.697484225822090.448393185
794557.629213929821445.111729131794892.602980616821729.880579564
795667.205797616821327.933095982  795553.3417207821799.087386061
796182.656583756821845.374039634796069.391396999822437.549721038
796199.092724801823099.892737894796910.040243924824384.615197327
796813.283290298824965.132340573795929.962048561825556.243230572
795851.831330955825936.500240019795969.018830987826413.930795601

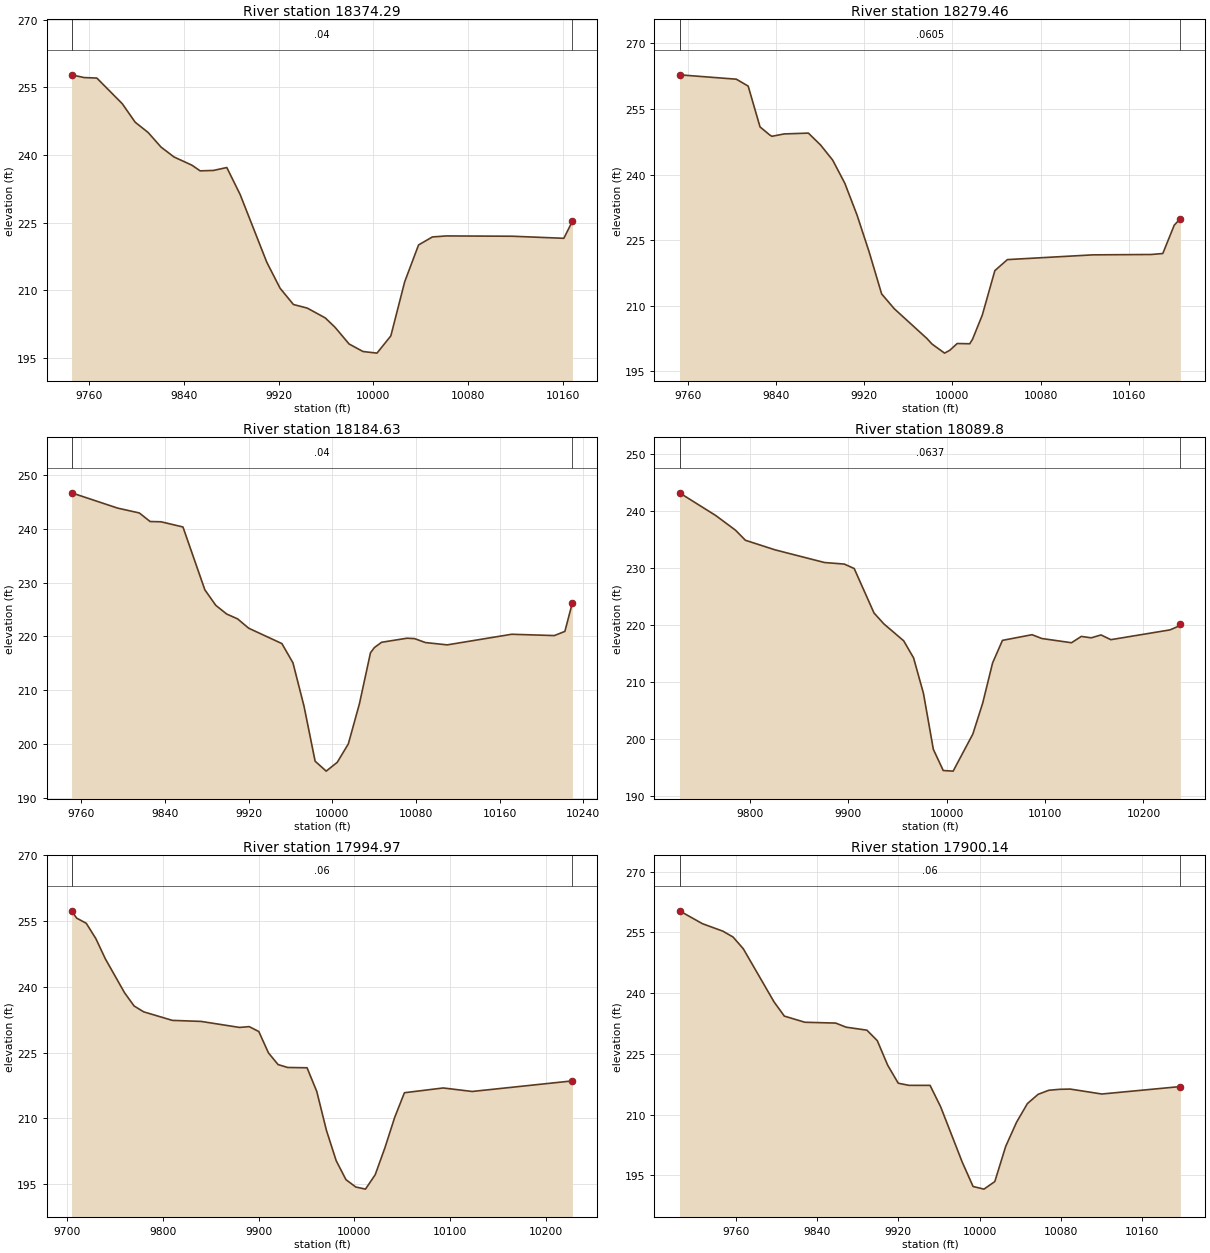
Type RM Length L Ch R = 1 ,18374.29,94.830200,94.830200,94.830200
XS GIS Cut Line= 6
785862.119860134824274.809808131785901.646025521824181.148035073
785941.477256847824103.918545731786010.847206117823991.033885767
786043.079844431823923.750364042786052.755708909823898.204090572
#Sta/Elev= 30
9745.172257.80369755.741257.19699766.515257.08439788.062251.36829798.841247.2896
9809.789245.01019820.737241.75419831.685239.56119846.851237.73019853.768236.4768
 9865.02236.57229876.272237.21599887.523231.23229910.027216.19149921.278210.4056
 9932.53206.80239944.239205.99869959.419203.82589967.768201.71639979.532198.0353
9991.296196.3612 10003.1196.0022 10014.8199.8288 10026.5211.8452 10038.2220.0186
 10049.9221.8044 10061.6222.025810117.29221.9621 10160.9221.499910168.17225.3012
#Mann= 3 , 0 , 0
9745.172    0.04       09745.172    0.04       010168.17    0.04       0
#XS Ineff= 2 , 0
       0                               0
Bank Sta=9745.172,10168.17
Exp/Cntr=0.3,0.1

Type RM Length L Ch R = 1 ,18279.46,94.830200,94.830200,94.830200
XS GIS Cut Line= 6
785952.586566522824323.320940545785981.768717509824246.715218854
786021.198101987824162.048478003786091.116530135824034.894346502
786118.314995957823972.477305364786138.364083302 823909.61854049
#Sta/Elev= 30
9752.279262.82869803.838261.83089814.597260.24949825.356 250.9159834.269249.0486
9836.162248.76569847.193249.30459869.255249.49599880.286 246.7789891.318243.3132
9902.349237.9967 9913.38230.76679924.411 222.2919935.721212.71199947.148209.3259
9976.859202.49599981.428201.24049992.855 199.1589997.526199.797910004.31201.3593
 10015.7201.299410018.24202.3386 10027.1207.870910038.49218.034310049.88220.5546
 10127.2 221.63810180.43221.724910190.92221.946810201.29228.423810206.87229.9173
#Mann= 3 , 0 , 0
9752.279  0.0605       09752.279  0.0605       010206.87  0.0605       0
#XS Ineff= 2 , 0
       0                               0
Bank Sta=9752.279,10206.87
Exp/Cntr=0.3,0.1

Type RM Length L Ch R = 1 ,18184.63,94.830100,94.830100,94.830100
XS GIS Cut Line= 6
786068.354096494824377.686578801786086.900116315824306.523557744
786113.651995341824219.741582198786163.561141024824076.891401389
786180.770046643824017.421184818786199.986760665823917.834897471
#Sta/Elev= 30
9750.595246.63289794.708243.79789815.376242.9014 9825.73241.31219836.194241.2635
9857.123240.30189878.052228.65779888.516225.7741 9898.98224.15879909.445223.2573
9919.971221.53589951.757 218.6829962.353215.10689972.948207.04139983.544196.8785
9994.139195.036210004.72196.673910015.31200.089110025.91 207.523 10036.5216.9848
10040.27217.952310047.09218.922910071.44 219.67910078.64219.607610089.05218.8744
10109.88218.443310171.53220.411910212.33220.167210222.42220.939510229.65226.2821
#Mann= 3 , 0 , 0
9750.595    0.04       09750.595    0.04       010229.65    0.04       0
#XS Ineff= 2 , 0
       0                               0
Bank Sta=9750.595,10229.65
Exp/Cntr=0.3,0.1

Type RM Length L Ch R = 1 , 18089.8,94.830200,94.830200,94.830200
XS GIS Cut Line= 6
786203.511363325824431.565424633786208.757632108 824388.18091499
 786233.58497835824162.387426781786235.051417907824149.800899127
786244.777426175824020.939271588786248.975055998823924.366670182
#Sta/Elev= 30
9728.145243.25059764.977239.26199785.106236.67749795.166234.90679825.347233.2206
9875.648 230.9929895.769230.71949905.829229.9337 9925.95222.1199 9936.01220.1961
9956.131217.22689966.191214.22759976.251207.98479986.311198.13879996.372194.4118
10006.44194.304310026.51200.833610036.54206.290110046.57213.3311 10056.6217.3011
10086.69218.296910096.71217.6282 10126.8216.885210136.83217.997910146.84217.7485
10156.85218.254510166.86217.424510226.92219.140610236.93219.879310237.56220.1954
#Mann= 3 , 0 , 0
9728.145  0.0637       09728.145  0.0637       010237.56  0.0637       0
#XS Ineff= 2 , 0
       0                               0
Bank Sta=9728.145,10237.56
Exp/Cntr=0.3,0.1

Type RM Length L Ch R = 1 ,17994.97,94.830100,94.830100,94.830100
XS GIS Cut Line= 6
786352.195046481824450.316674821 786346.95099526824288.641002433
786332.786712043824179.702216198786314.205295044824084.847675793
786303.240162665824003.492101263786297.211367387823930.798178366
#Sta/Elev= 30
9704.428257.34189709.745 255.6729719.746254.50259729.748251.0212 9739.75 246.376
9759.755238.66229769.757235.63169779.759234.2974 9809.77232.34589839.828232.1094
9879.959230.73589890.018230.92129900.077229.80519910.136224.94219920.195 222.268
9930.262221.60239950.512221.53039960.637216.14059970.762207.25039980.926200.3429
9991.133196.014710001.35194.335110011.53193.845510021.72197.1297 10031.9203.2988
10042.08210.216810052.26215.839810092.81216.926910123.08216.127810227.82218.5417
#Mann= 3 , 0 , 0
9704.428    0.06       09704.428    0.06       010227.82    0.06       0
#XS Ineff= 2 , 0
       0                               0
Bank Sta=9704.428,10227.82
Exp/Cntr=0.3,0.1

Type RM Length L Ch R = 1 ,17900.14,94.830200,94.830200,94.830200
XS GIS Cut Line= 6
786475.147459885824417.492671025786458.789423606824273.693317375
786445.567569477824211.773623543 786430.55415054824161.413148301
 786386.71725375824037.952667152786363.658236332823939.657760891
#Sta/Elev= 30
9704.868260.33499727.437257.15549747.505255.31779757.539253.86169767.588250.9737
9797.864237.84699807.956234.3456 9828.14232.82519858.533232.61839868.758231.6069
9889.209230.86689899.435228.2751 9909.66222.20949920.027217.77289930.462217.2481
9951.332217.23989961.767211.93639982.996198.27649993.649192.275110004.33191.6224
10015.02193.489510025.71202.1647 10036.4208.141910047.06212.738810057.58215.0257
 10068.1216.030210078.62216.263810089.14216.328410120.26215.105810197.55216.9463
#Mann= 3 , 0 , 0
9704.868    0.06       09704.868    0.06       010197.55    0.06       0
#XS Ineff= 2 , 0
       0                               0
Bank Sta=9704.868,10197.55
Exp/Cntr=0.3,0.1

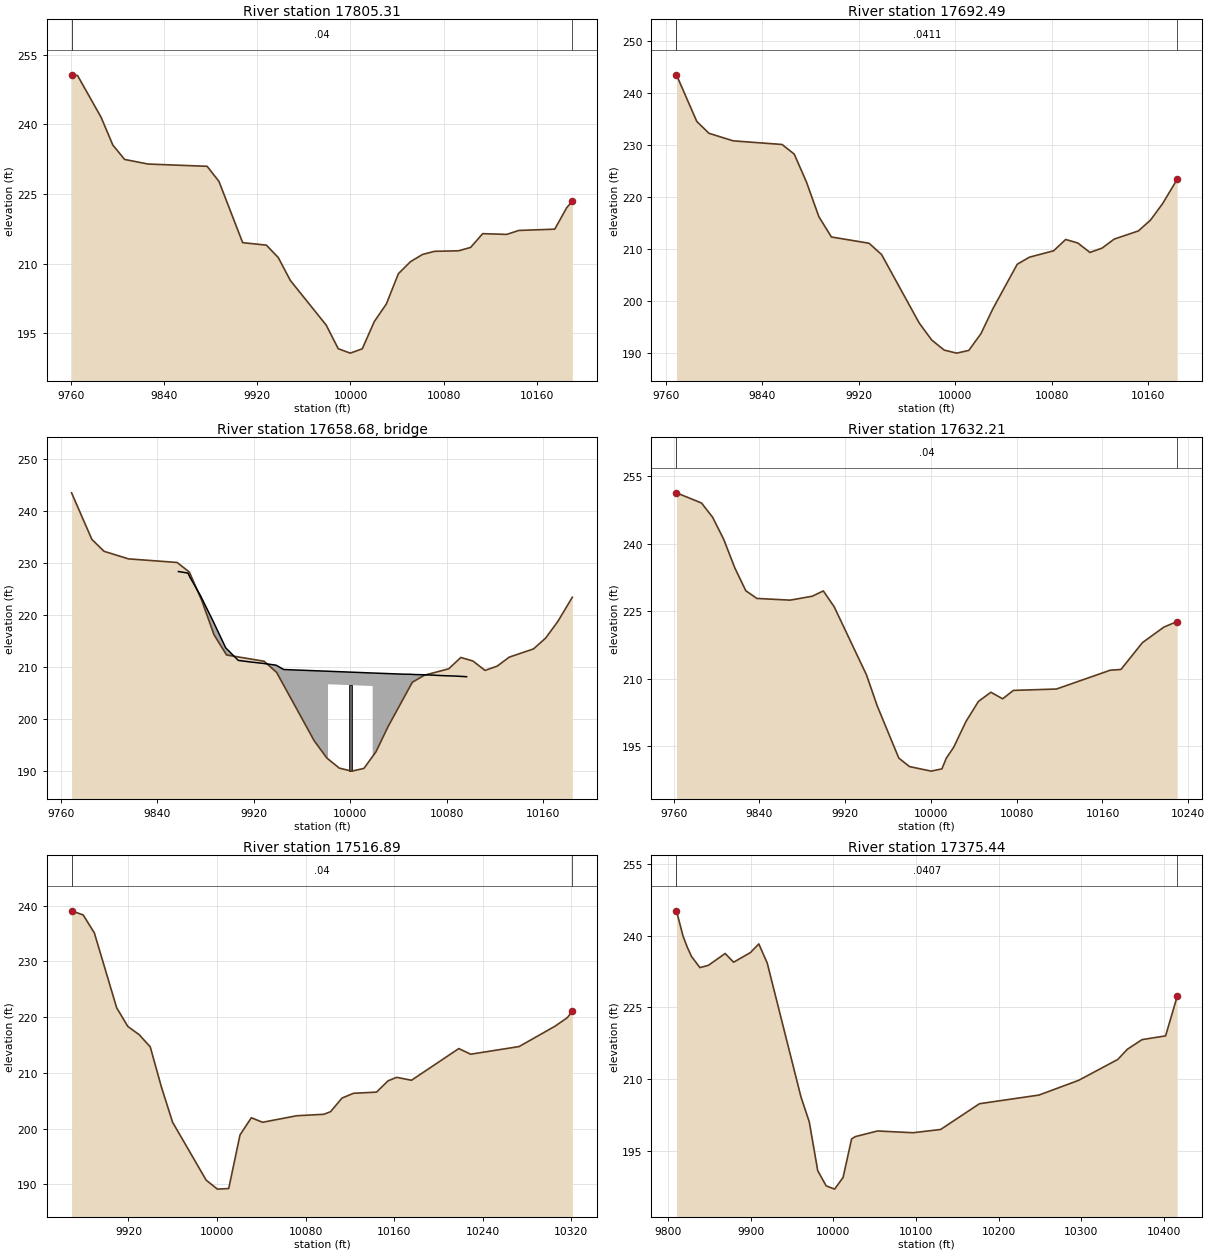
Type RM Length L Ch R = 1 ,17805.31,112.811900,112.811900,112.811900
XS GIS Cut Line= 6
786549.928840197824330.097084529 786537.85402848824240.521392628
786522.536743177824158.063790655786506.569289217824092.725531312
786471.253455631823957.624506556786459.887723086823910.324264335
#Sta/Elev= 30
9760.633250.62769765.777250.47619785.957241.49689796.048235.51489806.138232.4183
9826.319231.42439876.977 230.9379887.148 227.684 9907.49214.50049927.833  213.97
9938.042211.30079948.336 206.3969979.221196.74499989.515191.6752 9999.81190.7247
10010.13191.642510020.47197.517810030.81201.302610041.14207.820710051.48210.4016
10061.81211.956610072.15212.637110092.82212.752210103.16213.480310113.49 216.439
10134.17216.280410144.49217.129410175.34217.405610185.63222.024110190.44223.4584
#Mann= 3 , 0 , 0
9760.633    0.04       09760.633    0.04       010190.44    0.04       0
#XS Ineff= 2 , 0
       0                               0
Bank Sta=9760.633,10190.44
Exp/Cntr=0.3,0.1

Type RM Length L Ch R = 1 ,17692.49,60.288000,60.288000,60.288000
XS GIS Cut Line= 4
786569.488119655824301.643996475786585.221592724824192.675127566
786617.647712857 824077.70979251786635.334687442823892.979168683
#Sta/Elev= 30
9768.948243.40569785.765234.46159795.869232.16899816.076230.71649856.491230.0219
9866.594228.17249876.698222.81859887.022216.13679897.412212.24489928.582211.0422
9938.972208.87489970.143195.73069980.533192.45039990.923190.501810001.22189.9244
10011.27190.441210021.31193.641210031.36198.497310051.45207.003110061.49208.3555
10081.59209.588110091.63211.763210101.68211.087510111.72209.276210121.77210.1044
10131.81211.834410151.91213.410110161.95215.4921   10172 218.66910184.07223.3368
#Mann= 3 , 0 , 0
9768.948  0.0411       09768.948  0.0411       010184.07  0.0411       0
#XS Ineff= 2 , 0
       0                10066.56       0
Bank Sta=9768.948,10184.07
Exp/Cntr=0.3,0.1

Type RM Length L Ch R = 3 ,17658.68,,,
BEGIN DESCRIPTION:
END DESCRIPTION:
Bridge Culvert--1,0,-1,-1, 0
Deck Dist Width WeirC Skew NumUp NumDn MinLoCord MaxHiCord MaxSubmerge Is_Ogee
17.644000,25.000000,2.6,0, 29, 29, , , 0.95, 0, 0,0,,
 9857.54 9865.44 9867.09 9875.86 9886.29 9896.71 9902.45 9907.14 9917.57 9927.41
 9927.99 9938.37 9938.41 9944.83 9981.54 9981.5410018.5410018.5410045.8210047.95
10048.4410053.3510065.2210066.7610077.0810085.1410085.2910089.5610096.39
  228.28  227.98  227.19  223.62  218.73  213.62  212.29  211.20  210.89  210.64
  210.62  210.29  210.29  209.45  209.12  209.12  208.78  208.78  208.54  208.55
  208.55  208.49  208.41  208.39  208.27  208.21  208.21  208.16  208.07
 -771.72 -772.02 -772.81 -776.38 -781.27 -786.38 -787.71 -788.80 -789.11 -789.36
 -789.38 -789.71 -789.71 -790.55 -790.88  206.62  206.28 -791.22 -791.46 -791.45
 -791.45 -791.51 -791.59 -791.61 -791.73 -791.79 -791.79 -791.84 -791.93
 9857.54 9865.44 9867.09 9875.86 9886.29 9896.71 9902.45 9907.14 9917.57 9927.41
 9927.99 9938.37 9938.41 9944.83 9971.94 9971.9410008.9410008.9410045.8210047.95
10048.4410053.3510065.2210066.7610077.0810085.1410085.2910089.5610096.39
  228.28  227.98  227.19  223.62  218.73  213.62  212.29  211.20  210.89  210.64
  210.62  210.29  210.29  209.45  209.20  209.20  208.87  208.87  208.54  208.55
  208.55  208.49  208.41  208.39  208.27  208.21  208.21  208.16  208.07
 -771.72 -772.02 -772.81 -776.38 -781.27 -786.38 -787.71 -788.80 -789.11 -789.36
 -789.38 -789.71 -789.71 -790.55 -790.80  206.70  206.37 -791.13 -791.46 -791.45
 -791.45 -791.51 -791.59 -791.61 -791.73 -791.79 -791.79 -791.84 -791.93
Pier Skew, UpSta & Num, DnSta & Num=  ,10000.04, 2 ,9990.44, 2 , 0 , 0 , 0 ,,
    2.00    2.00
 -791.05  208.95
    2.00    2.00
 -790.96  209.04
BR Coef=-1 , 0 , 0 ,, 0 ,,,0.8,0,1,0,
WSPro=,,,, 1 ,,,, 0 ,,,, 0 ,,,,-1 ,-1 ,-1 , 0 , 0 , 0 , 0 , 0
BC Design=,, 0 ,, 0 ,,,,,,

Type RM Length L Ch R = 1 ,17632.21,115.312300,115.312300,115.312300
XS GIS Cut Line= 5
786633.369468093824307.640462622786667.760807604824174.005543262
786679.552124053824061.005427599786704.117366582824018.753210455
786691.343440443823852.692170933
#Sta/Elev= 30
9762.674  251.349786.052249.07439796.378245.91749806.704241.01889817.029 234.689
9827.355229.56619837.681227.85119868.659227.4734 9889.31228.34389899.636229.5216
9909.718226.0255 9939.88210.86479949.935203.95019970.043192.34429980.098190.4481
10000.21189.445510010.26189.949510014.28192.296210021.22194.749310032.79200.5264
10044.36204.959110055.93206.988110066.92205.533610076.94207.399910117.06207.7042
10167.21211.886210177.24212.0558 10197.3218.029410217.36221.4904 10229.7222.7195
#Mann= 3 , 0 , 0
9762.674    0.04       09762.674    0.04       0 10229.7    0.04       0
#XS Ineff= 2 , 0
       0                               0
Bank Sta=9762.674,10229.7
Exp/Cntr=0.3,0.1

Type RM Length L Ch R = 1 ,17516.89,141.453200,141.453200,141.453200
XS GIS Cut Line= 6
786810.859744506824195.430522545786794.833965675824076.823080787
 786773.30946753823970.769624719786747.185260218823884.000972283
786724.725931451823826.606747491786695.517992403823760.765282058
#Sta/Elev= 30
9868.637239.05279879.142238.31099889.214 235.0889909.367221.66129919.468218.3033
9929.568216.86259939.668214.66139949.768207.45479959.869 201.1339990.181190.7493
10000.34189.136110010.55189.245510020.76198.865610030.97201.935610041.18201.1261
10071.81202.295210096.55202.560110102.53203.030610112.89205.470210123.25206.3236
10144.02206.535410154.55208.576210162.27209.185410175.61208.664410218.34214.3448
10229.08213.337510272.81214.709510305.28 218.36310316.22 219.87110320.86221.0037
#Mann= 3 , 0 , 0
9868.637    0.04       09868.637    0.04       010320.86    0.04       0
#XS Ineff= 2 , 0
       0                               0
Bank Sta=9868.637,10320.86
Exp/Cntr=0.3,0.1

Type RM Length L Ch R = 1 ,17375.44,141.453100,141.453100,141.453100
XS GIS Cut Line= 6
786967.515194672824222.907584482786930.980870831824035.413041302
786908.531758188823959.792652505786887.539323443823916.423553525
786783.308737519823756.503429081786734.154524665823672.742951223
#Sta/Elev= 30
9809.976245.21829818.028239.8779  9823.3237.50629828.211235.65329838.395233.3264
9848.578233.79539868.944 236.2879879.127 234.4569899.493236.47379909.676238.2861
9919.859234.28469960.592206.31729970.781200.99939980.993190.80819991.204187.6252
10001.42 186.93510011.71189.3888   10022197.456310026.48197.933810053.41199.1118
10096.37198.745710129.79199.427310176.82204.824910248.83206.634110296.83 209.716
10344.18214.085810355.88216.230710373.61218.246410402.12219.028810416.17227.3258
#Mann= 3 , 0 , 0
9809.976  0.0407       09809.976  0.0407       010416.17  0.0407       0
#XS Ineff= 2 , 0
       0                               0
Bank Sta=9809.976,10416.17
Exp/Cntr=0.3,0.1

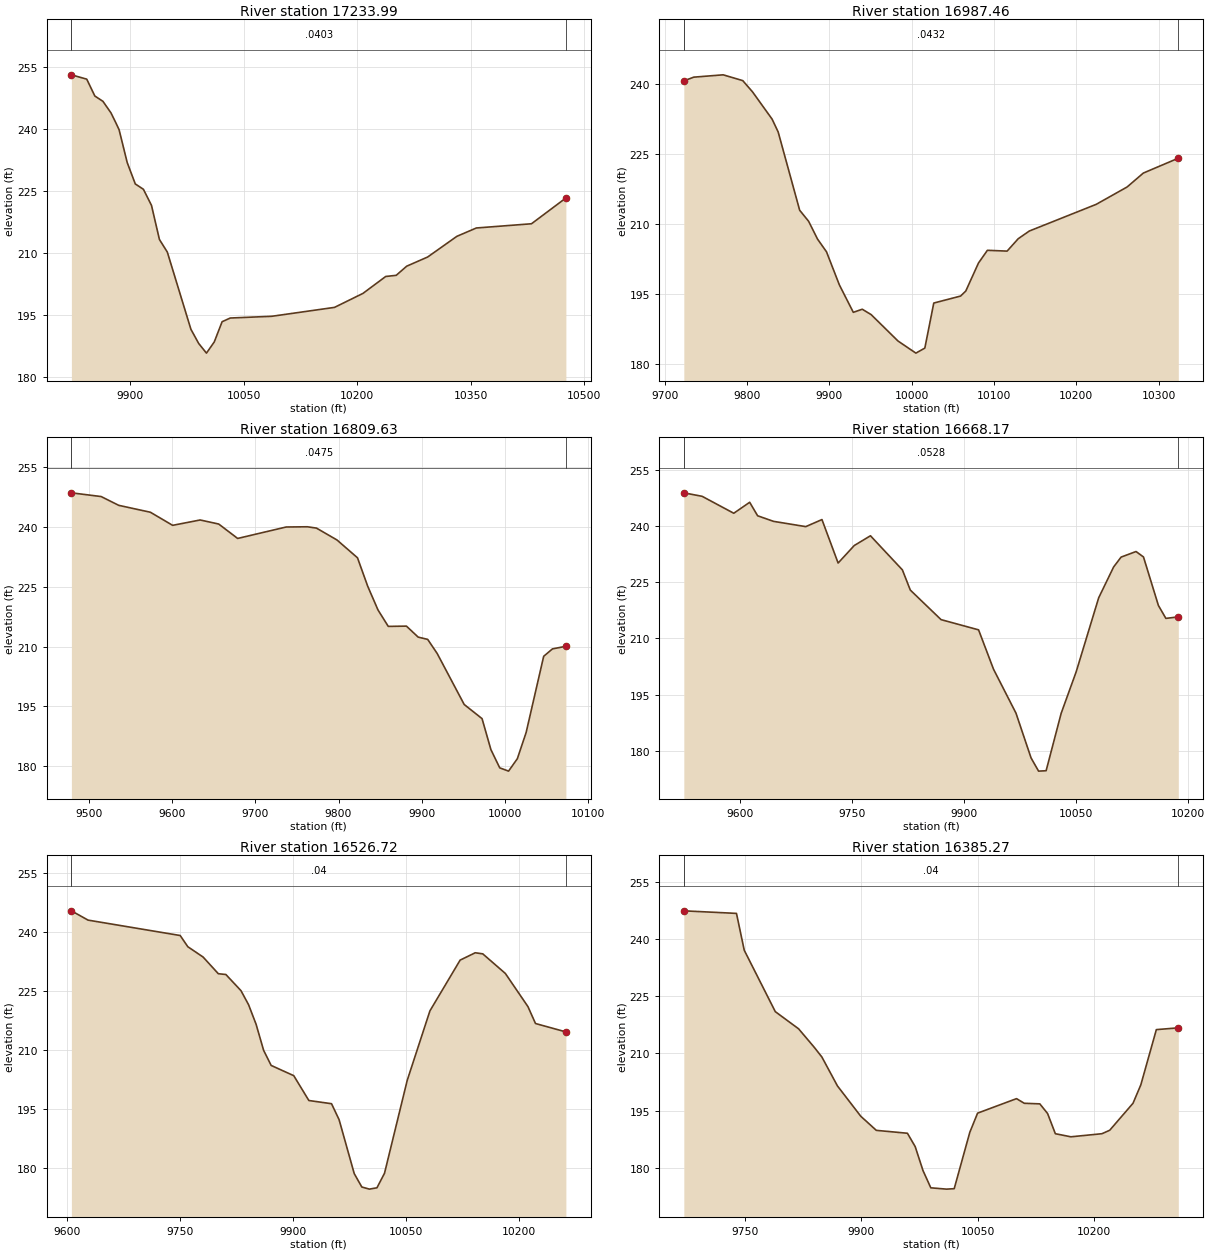
Type RM Length L Ch R = 1 ,17233.99,246.529900,246.529900,246.529900
XS GIS Cut Line= 6
787125.990450043824173.982337853787054.222510622823963.117115784
787040.601254821823947.625168236786903.789064324823845.478768376
786823.709874424823754.077037047 786759.05981764823656.425690311
#Sta/Elev= 30
9822.342253.08179842.642252.03469853.336247.95659864.029246.67539874.723243.8595
9881.579241.29959885.417239.79369896.111231.86589906.805226.68529917.499225.4016
9928.193221.5229  9938.7213.25489949.164210.19489980.315191.53649990.594 188.105
10000.87185.762510011.21188.473310021.56193.357410032.33194.254110087.21194.6723
10170.16196.829210207.71200.208710237.84204.3029 10251.7204.582510265.55206.7938
 10293.2209.008410331.85214.011510357.61216.032710430.47217.052810475.96223.2834
#Mann= 3 , 0 , 0
9822.342  0.0403       09822.342  0.0403       010475.96  0.0403       0
#XS Ineff= 2 , 0
       0                               0
Bank Sta=9822.342,10475.96
Exp/Cntr=0.3,0.1

Type RM Length L Ch R = 1 ,16987.46,177.829700,177.829700,177.829700
XS GIS Cut Line= 6
787287.151044369 823985.16492486787219.224179596 823879.87828441
786983.360926628823779.789480641786938.403191149823739.081407979
786902.597712845 823699.34524551786841.575609177823613.768074051
#Sta/Elev= 30
 9723.08 240.7579735.177241.55399770.878242.0538 9794.68 240.813 9806.58238.3899
9830.381232.53939837.723229.79049863.829213.00699874.692210.63679885.555206.8126
9896.418 204.0929912.064196.99159929.008191.09939939.871191.76999950.734190.6039
9983.323 184.94610005.05182.348910015.91183.427810026.78193.091410059.37194.5935
10065.66195.668710081.09201.675110091.95204.409210115.88204.233910129.37206.8926
10142.86208.543610224.17214.270310261.67217.991310281.39220.9779 10323.9224.1683
#Mann= 3 , 0 , 0
 9723.08  0.0432       0 9723.08  0.0432       0 10323.9  0.0432       0
#XS Ineff= 2 , 0
       0                               0
Bank Sta=9723.08,10323.9
Exp/Cntr=0.3,0.1

Type RM Length L Ch R = 1 ,16809.63,141.453100,141.453100,141.453100
XS GIS Cut Line= 6
787448.041459677824168.752294022787422.483168383824096.996003669
787376.781270382823997.861637333787329.890756584823920.579600808
787236.356293463823783.855322123787183.231109313823639.722057653
#Sta/Elev= 30
9478.355248.57669514.185247.64099535.415 245.4359573.482 243.7079600.236 240.423
9633.427241.7666 9655.76 240.7479678.539237.13529736.981240.00569762.492 240.061
9773.406239.72969798.111236.75429822.816232.28149835.168225.12439847.521219.1908
9859.873215.07749881.733215.14549895.903212.38569907.318211.81889918.732208.2936
9951.296195.48999972.778191.94419983.426184.17759994.075 179.60110004.69178.7786
10015.26181.890310025.84188.452510046.98207.580310057.55 209.43610073.71210.0825
#Mann= 3 , 0 , 0
9478.355  0.0475       09478.355  0.0475       010073.71  0.0475       0
#XS Ineff= 2 , 0
       0                               0
Bank Sta=9478.355,10073.71
Exp/Cntr=0.3,0.1

Type RM Length L Ch R = 1 ,16668.17,141.453200,141.453200,141.453200
XS GIS Cut Line= 6
787461.822055359824158.454706038787364.886332443823906.500550466
 787343.35939226 823832.02721039787339.551754369823770.330274932
787355.367587207823628.219892723787356.152890899823518.342318555
#Sta/Elev= 30
9524.117248.8078 9548.65247.87739591.053243.36259612.355246.28799623.006242.6899
9644.308241.20399687.535239.79979709.199241.68119730.862230.09099752.525234.7676
9774.188237.36059816.997228.26339827.587222.88949868.787215.00799919.071212.2827
9939.087201.79569969.197190.07599989.381 178.1519999.474174.625810009.57174.7301
10029.76190.049910049.88201.1225   10080220.821510100.01229.039310110.02231.6729
10130.04233.161310140.04231.711510160.04218.778510170.04215.338510186.71215.7331
#Mann= 3 , 0 , 0
9524.117  0.0528       09524.117  0.0528       010186.71  0.0528       0
#XS Ineff= 2 , 0
       0                               0
Bank Sta=9524.117,10186.71
Exp/Cntr=0.3,0.1

Type RM Length L Ch R = 1 ,16526.72,141.453200,141.453200,141.453200
XS GIS Cut Line= 6
787517.856315298824116.582951353787497.901684389824025.576407267
787478.188758108823881.053408432787480.641442673 823781.20218727
787498.176196864823577.537114416787498.175547409823464.689314993
#Sta/Elev= 30
9605.982245.29659628.078242.93759750.415239.02129760.551236.17359780.823233.5552
9801.026229.3174 9811.06229.11459831.128225.00639841.162221.45479851.176216.4663
9861.176209.84629871.176206.01689901.176203.41339921.213197.10559951.293 196.295
9961.343192.23979981.444178.53299991.494175.131910001.54174.591410011.59174.9285
10021.63178.622110051.77202.219210081.91219.875110122.01232.772310142.04234.6394
10152.05234.367110182.06229.381910212.06 220.95210222.06216.665810262.39214.5347
#Mann= 3 , 0 , 0
9605.982    0.04       09605.982    0.04       010262.39    0.04       0
#XS Ineff= 2 , 0
       0                               0
Bank Sta=9605.982,10262.39
Exp/Cntr=0.3,0.1

Type RM Length L Ch R = 1 ,16385.27,141.453100,141.453100,141.453100
XS GIS Cut Line= 6
787618.214817862824052.737212202787614.529170582823970.480273296
787615.960677697823879.003404435787632.618835231 823645.14352749
787637.128667366823538.025205426787632.904535421823416.783137426
#Sta/Elev= 30
9671.598247.36249739.413246.68969749.421237.02919789.429220.92169819.433216.4202
9839.435211.61139849.441209.02139869.467  201.459899.505193.49499919.531 189.793
9959.582189.0362 9969.61185.52999979.662179.24759989.714174.727610009.81174.3821
10019.85174.494310039.93189.268210049.97194.3062 10100.1198.110710110.11 196.894
10130.13196.741610140.14194.209710150.15188.910110170.16188.103710210.18188.9131
10220.18189.822910250.18196.9046 10260.2201.713510280.23216.212910308.52216.6709
#Mann= 3 , 0 , 0
9671.598    0.04       09671.598    0.04       010308.52    0.04       0
#XS Ineff= 2 , 0
       0                10066.49       0
Bank Sta=9671.598,10308.52
Exp/Cntr=0.3,0.1

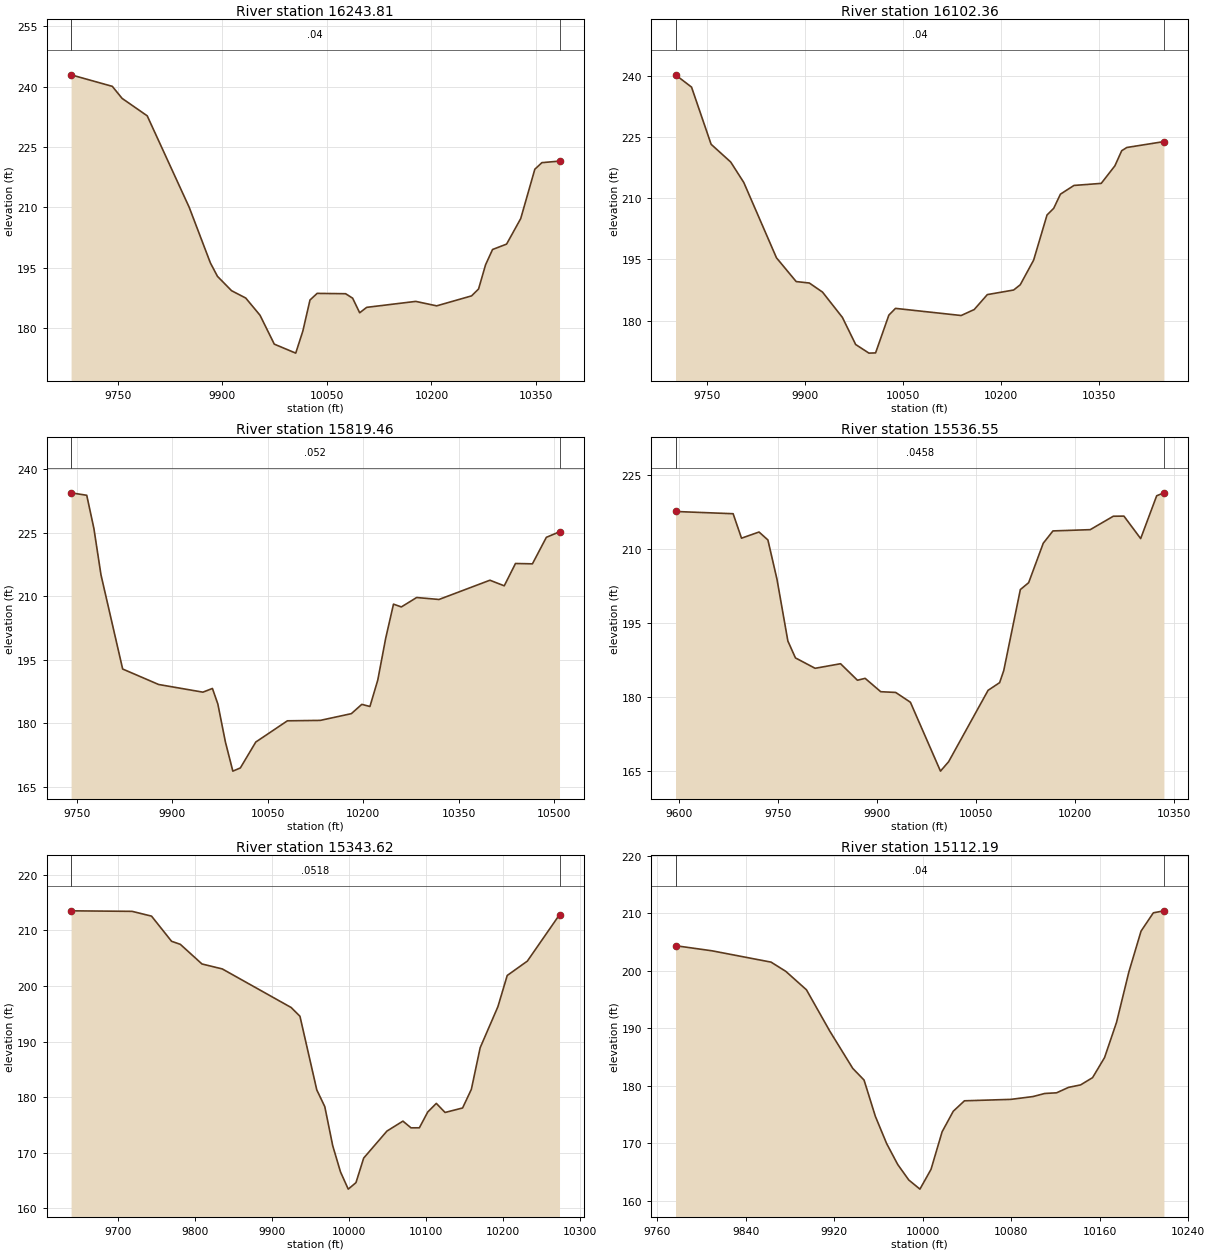
Type RM Length L Ch R = 1 ,16243.81,141.453200,141.453200,141.453200
XS GIS Cut Line= 6
787727.185609108824064.141132216787735.534804053823901.425625526
 787789.49277755823611.581811577 787791.74171012823526.252819716
787785.232858583823451.980499862 787770.62009824823370.275914569
#Sta/Elev= 30
9682.825242.96259741.979240.09889755.995237.1131 9792.11232.76529852.382210.0108
9882.775196.18849892.906192.85529913.167189.28129933.502187.45719954.003183.1819
9974.505175.989510005.26173.757710015.49179.257310025.73186.964810035.96188.6145
10076.85188.530310086.94187.422410097.04183.794510107.14185.140710177.51186.6226
10207.53185.512710257.65187.993210267.69189.709510277.73195.722810287.77199.5278
10307.91200.867210328.18207.212610348.45219.487810358.59221.124410383.86221.5087
#Mann= 3 , 0 , 0
9682.825    0.04       09682.825    0.04       010383.86    0.04       0
#XS Ineff= 2 , 0
       0                10051.53       0
Bank Sta=9682.825,10383.86
Exp/Cntr=0.3,0.1

Type RM Length L Ch R = 1 ,16102.36,282.906300,282.906300,282.906300
XS GIS Cut Line= 6
787876.123151592824079.561698994787880.989684973823916.593052037
787912.149549739823728.980131417787918.136945904823614.035657266
 787894.63010253 823485.77191759787849.035164776823343.794760951
#Sta/Elev= 30
9701.549240.17339726.113237.16789756.116223.16319786.149218.82249806.184 213.814
9856.272195.36469886.475189.54979906.649189.19099926.823186.96929957.276180.7766
9977.621174.13629997.966172.026910008.14172.083410028.48181.334210038.65182.9834
10139.28181.237510159.29 182.70210179.36186.356610219.67187.4789 10229.8188.7629
10250.32194.807510270.84205.8499 10281.1207.492510291.36210.946310312.09213.0855
10353.92213.592910374.83217.890610385.29221.591910393.13222.380410449.97223.8233
#Mann= 3 , 0 , 0
9701.549    0.04       09701.549    0.04       010449.97    0.04       0
#XS Ineff= 2 , 0
       0                 10057.1       0
Bank Sta=9701.549,10449.97
Exp/Cntr=0.3,0.1

Type RM Length L Ch R = 1 ,15819.46,282.906400,282.906400,282.906400
XS GIS Cut Line= 6
 788300.22856808823977.440320212788259.147959778823892.829986286
788172.748305932823746.118964402788010.735692651823535.362131592
787970.617474574823469.327867154 787901.32514834823326.136176336
#Sta/Elev= 30
9741.154234.40969765.738 233.8299776.916226.03049788.094215.02739822.134192.7738
9878.633189.11739948.134187.30719963.064 188.1819971.614184.48149983.355175.5831
9995.095168.645710006.88169.399310031.13175.518510080.75180.535110132.42180.6365
10181.17182.226810197.57184.425910210.34183.918810222.67190.180210235.01199.9948
10247.34208.104310259.67207.445610283.68209.670310318.78209.2095 10398.7 213.758
 10421.2 212.43610438.86217.710710465.45217.628410487.33223.896410507.96225.1929
#Mann= 3 , 0 , 0
9741.154   0.052       09741.154   0.052       010507.96   0.052       0
#XS Ineff= 2 , 0
       0                   10119       0
Bank Sta=9741.154,10507.96
Exp/Cntr=0.3,0.1

Type RM Length L Ch R = 1 ,15536.55,192.931400,192.931400,192.931400
XS GIS Cut Line= 6
788560.743592011823775.751269411 788450.65147013823638.451010432
788373.137087849823573.744689245788274.143415048823520.614804711
788142.279418941823429.156436833 788020.30569171823285.955861687
#Sta/Elev= 30
 9594.88217.56919682.091217.11519694.789 212.1549721.295213.40449734.735211.7967
  9748.5203.81249764.951191.30459776.418187.87389806.201185.76569844.706186.6902
9870.276183.34369881.922183.72669905.498181.0167 9928.15180.86819950.433178.8784
9995.948164.908810008.28166.815610067.99181.292110085.49182.855310091.74185.3109
10116.86201.730410129.42203.126710151.51211.124310166.22213.627110222.61213.8825
10257.56216.604910273.64216.631810298.98212.072710323.22220.755410334.18221.3527
#Mann= 3 , 0 , 0
 9594.88  0.0458       0 9594.88  0.0458       010334.18  0.0458       0
#XS Ineff= 2 , 0
       0                               0
Bank Sta=9594.88,10334.18
Exp/Cntr=0.3,0.1

Type RM Length L Ch R = 1 ,15343.62,231.428100,231.428100,231.428100
XS GIS Cut Line= 6
788619.665227281823730.134519522788554.335763511823638.893338969
788447.372112531823511.127505266 788423.93112723823454.068675124
788408.095276412823355.672124265788313.208449567823187.041159848
#Sta/Elev= 30
9638.928213.51529718.205213.42139743.498 212.561 9769.53208.03259780.908207.4876
9809.065203.95069835.422203.06189924.952196.11969936.393194.54349958.273181.2929
9968.667178.28479979.008171.23819989.087166.53649999.139163.437310009.19164.6022
10019.23169.025510049.51 173.88810070.24175.673610080.74174.466210091.61174.4738
10102.49177.316110113.63178.865710125.02177.232510147.78178.039410159.17181.3961
10170.63188.887210193.65196.257610205.79201.881410231.98204.472710273.74212.8121
#Mann= 3 , 0 , 0
9638.928  0.0518       09638.928  0.0518       010273.74  0.0518       0
#XS Ineff= 2 , 0
       0                               0
Bank Sta=9638.928,10273.74
Exp/Cntr=0.3,0.1

Type RM Length L Ch R = 1 ,15112.19,456.215900,456.215900,456.215900
XS GIS Cut Line= 6
788660.688622644823515.620035468788606.276571935823365.364135096
788595.623787714823280.137457562 788584.23128426823224.014759952
788573.455102327823191.467134789788531.196756713823096.382511215
#Sta/Elev= 30
9776.341204.3959 9809.38203.50359862.777201.53229876.006199.93769894.729196.7226
9915.802189.54249936.615  183.049946.831 181.0089957.047174.69919967.218169.9687
9977.261166.31619987.303163.60749997.345162.024710007.37165.4642 10017.4 172.004
10027.48175.576410037.61177.3978 10079.6177.646110099.63178.137910110.16178.6715
 10120.9178.787810131.75179.737810142.59180.163110153.44181.425210164.29184.9211
10175.13191.061910186.24199.801910197.29206.9334 10208.4210.115510217.97210.4627
#Mann= 3 , 0 , 0
9776.341    0.04       09776.341    0.04       010217.97    0.04       0
#XS Ineff= 2 , 0
       0                               0
Bank Sta=9776.341,10217.97
Exp/Cntr=0.3,0.1