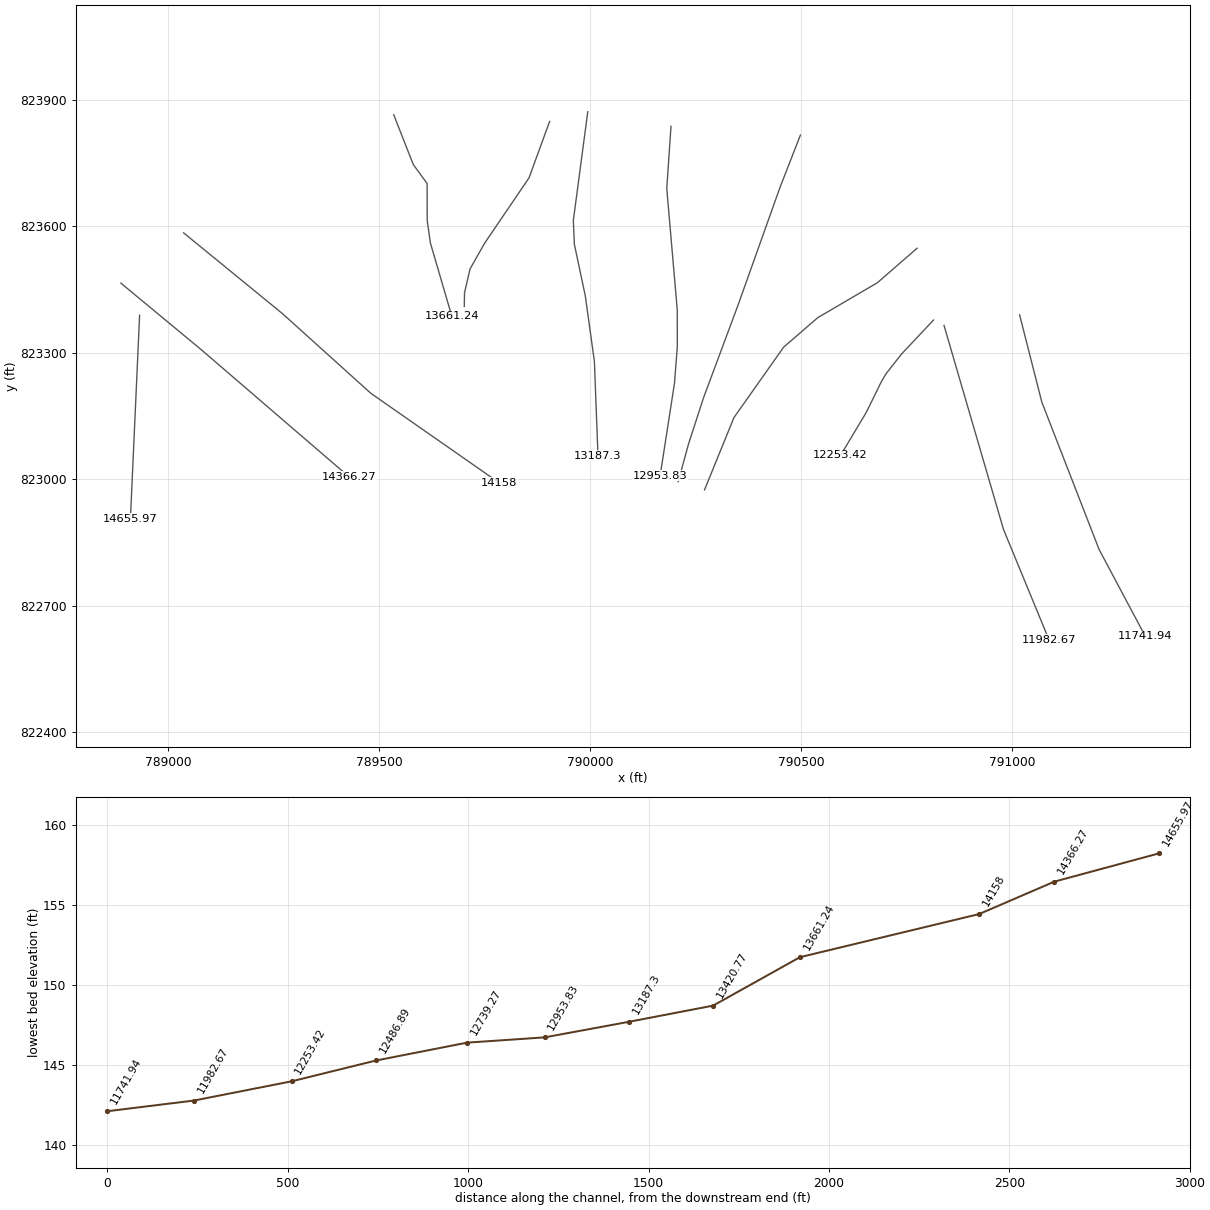
HEC-RAS study 18193_ras.prj: 18193

--- 18193_ras.g01 (geometry) --- (continued)

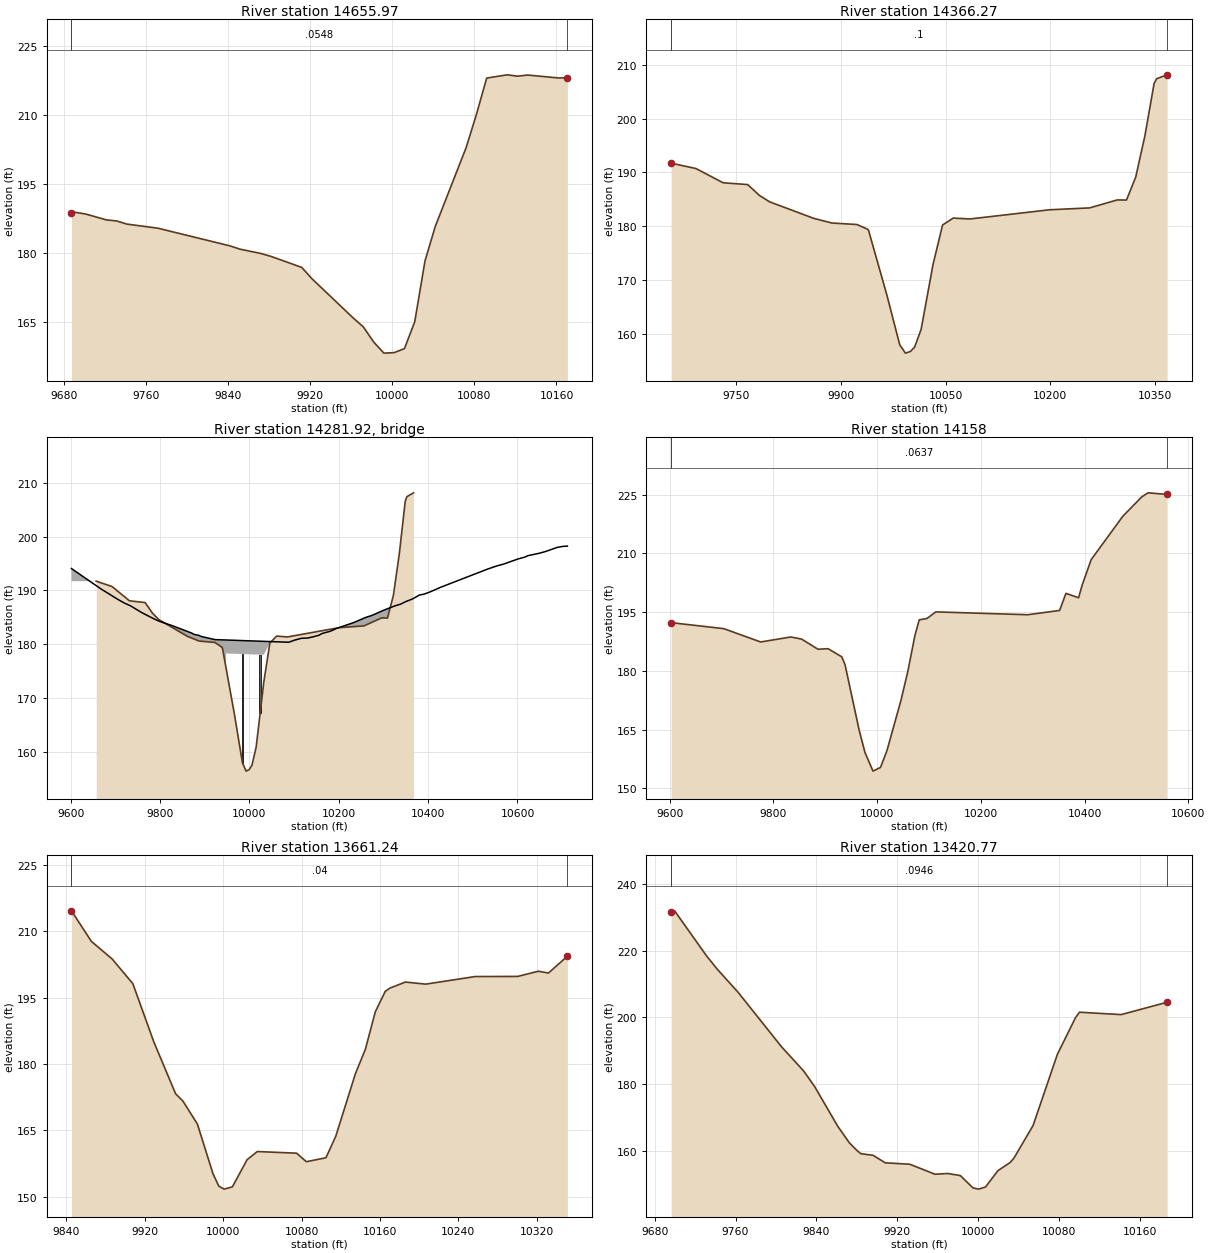
Type RM Length L Ch R = 1 ,14655.97,289.702000,289.702000,289.702000
XS GIS Cut Line= 2
 788931.98581031823389.005008385788910.205507249 822906.48752588
#Sta/Elev= 30
9687.619188.76019691.628188.85389701.639188.48559721.659187.21189731.669186.9859
9741.679186.2966 9771.71 185.4129841.781181.57289851.791180.83969871.812179.9175
9881.822179.28049911.852176.87929921.863174.40929961.903165.88779971.913163.9201
9981.924160.63719991.934158.209710001.94158.311810011.95159.193810021.96165.0378
10031.97178.293710041.98185.807710072.02202.949810082.03210.165610092.04218.0921
10112.06218.798810122.07218.505210132.08218.748510162.11218.115110170.63218.1561
#Mann= 3 , 0 , 0
9687.619  0.0548       09687.619  0.0548       010170.63  0.0548       0
#XS Ineff= 2 , 0
       0                               0
Bank Sta=9687.619,10170.63
Exp/Cntr=0.3,0.1

Type RM Length L Ch R = 1 ,14366.27,208.274900,208.274900,208.274900
XS GIS Cut Line= 3
788887.670824073823464.922044646789079.679696292823305.899312019
789429.072057396  823005.3350759
#Sta/Elev= 30
9657.066191.71829692.551190.72479731.504188.07929766.687187.74449783.441185.7333
9798.042184.54199861.347181.47049887.315180.60689923.089180.32899938.423179.4574
9939.776179.23439966.158167.16019984.425157.9893 9992.54156.44589999.759156.7567
10005.73157.561310015.09160.888810032.11172.920210045.76180.236410061.09181.5275
10084.88181.3594 10199.1183.066810256.36183.414110295.93184.895110309.12184.8674
10322.32189.114810335.51196.7946 10348.7206.534910352.44 207.41310367.26208.1271
#Mann= 3 , 0 , 0
9657.066     0.1       09657.066     0.1       010367.26     0.1       0
#XS Ineff= 2 , 0
       0                               0
Bank Sta=9657.066,10367.26
Exp/Cntr=0.3,0.1

Type RM Length L Ch R = 3 ,14281.92,,,
BEGIN DESCRIPTION:
END DESCRIPTION:
Bridge Culvert--1,0,-1,-1, 0
Deck Dist Width WeirC Skew NumUp NumDn MinLoCord MaxHiCord MaxSubmerge Is_Ogee
73.637450,61.000000,2.6,0, 50, 50, , , 0.95, 0, 0,0,,
 9601.73 9667.95 9707.43 9720.59 9733.75 9760.07 9786.39 9799.55 9825.03 9871.18
 9875.96 9886.50 9891.74 9922.89 9947.49 9947.4910061.4910061.4910088.1510100.63
10116.2610129.3410142.4310155.5210162.6310181.6910194.7810234.0510260.2210273.31
10302.1410325.5610338.5210349.1210364.8410380.5710390.3510403.3110427.7410532.89
10553.5310569.2510600.7010616.4210623.6010649.5210663.6010688.3910701.3510711.66
  194.07  190.27  188.24  187.64  187.15  185.84  184.72  184.23  183.53  182.07
  181.84  181.67  181.46  180.87  180.80  180.80  180.46  180.46  180.38  180.76
  181.11  181.15  181.38  181.68  182.00  182.44  182.94  184.05  184.99  185.33
  186.38  187.13  187.46  187.90  188.41  189.15  189.30  189.69  190.58  193.96
  194.55  194.90  195.83  196.19  196.46  196.92  197.25  197.98  198.18  198.23
 -805.93 -809.73 -811.76 -812.36 -812.85 -814.16 -815.28 -815.77 -816.47 -817.93
 -818.16 -818.33 -818.54 -819.13 -819.20  178.30  177.96 -819.54 -819.62 -819.24
 -818.89 -818.85 -818.62 -818.32 -818.00 -817.56 -817.06 -815.95 -815.01 -814.67
 -813.62 -812.87 -812.54 -812.10 -811.59 -810.85 -810.70 -810.31 -809.42 -806.04
 -805.45 -805.10 -804.17 -803.81 -803.54 -803.08 -802.75 -802.02 -801.82 -801.77
 9601.73 9667.95 9707.43 9720.59 9733.75 9760.07 9786.39 9799.55 9825.03 9871.18
 9875.96 9886.50 9891.74 9922.89 9949.42 9949.4210063.4210063.4210088.1510100.63
10116.2610129.3410142.4310155.5210162.6310181.6910194.7810234.0510260.2210273.31
10302.1410325.5610338.5210349.1210364.8410380.5710390.3510403.3110427.7410532.89
10553.5310569.2510600.7010616.4210623.6010649.5210663.6010688.3910701.3510711.66
  194.07  190.27  188.24  187.64  187.15  185.84  184.72  184.23  183.53  182.07
  181.84  181.67  181.46  180.87  180.79  180.79  180.45  180.45  180.38  180.76
  181.11  181.15  181.38  181.68  182.00  182.44  182.94  184.05  184.99  185.33
  186.38  187.13  187.46  187.90  188.41  189.15  189.30  189.69  190.58  193.96
  194.55  194.90  195.83  196.19  196.46  196.92  197.25  197.98  198.18  198.23
 -805.93 -809.73 -811.76 -812.36 -812.85 -814.16 -815.28 -815.77 -816.47 -817.93
 -818.16 -818.33 -818.54 -819.13 -819.21  178.29  177.95 -819.55 -819.62 -819.24
 -818.89 -818.85 -818.62 -818.32 -818.00 -817.56 -817.06 -815.95 -815.01 -814.67
 -813.62 -812.87 -812.54 -812.10 -811.59 -810.85 -810.70 -810.31 -809.42 -806.04
 -805.45 -805.10 -804.17 -803.81 -803.54 -803.08 -802.75 -802.02 -801.82 -801.77
Pier Skew, UpSta & Num, DnSta & Num=  ,9984.99, 2 ,9986.92, 2 , 0 , 0 , 0 ,,
    3.00    3.00
 -819.31  180.69
    3.00    3.00
 -819.32  180.68
Pier Skew, UpSta & Num, DnSta & Num=  ,10023.99, 2 ,10025.92, 2 , 0 , 0 , 0 ,,
    3.00    3.00
 -819.43  180.57
    3.00    3.00
 -819.44  180.56
BR Coef=-1 , 0 , 0 ,, 0 ,,,0.8,0,1,0,
WSPro=,,,, 1 ,,,, 0 ,,,, 0 ,,,,-1 ,-1 ,-1 , 0 , 0 , 0 , 0 , 0
BC Design=,, 0 ,, 0 ,,,,,,

Type RM Length L Ch R = 1 ,   14158,496.761200,496.761200,496.761200
XS GIS Cut Line= 4
789036.310187758823584.179208527789270.651918471823392.704867557
789480.070321262823203.902784213789784.974835157822991.229173109
#Sta/Elev= 30
9602.885192.32379704.502190.79219775.439187.39169833.638188.66529854.463188.1262
9886.072185.53369905.504185.67869931.945183.59959938.287181.55739965.215165.0079
9976.748  159.149992.143154.420710006.62 155.38310019.07159.6683   10046172.4485
10059.46 179.97210072.93189.029410081.29 193.04210096.22193.385110113.32195.0748
10290.43194.343310351.98195.441410364.17199.801510388.55198.6808 10395.3201.8404
10412.78208.3951 10473.9219.490710510.48224.437710522.67225.467410559.21225.0655
#Mann= 3 , 0 , 0
9602.885  0.0637       09602.885  0.0637       010559.21  0.0637       0
#XS Ineff= 2 , 0
       0                               0
Bank Sta=9602.885,10559.21
Exp/Cntr=0.3,0.1

Type RM Length L Ch R = 1 ,13661.24,240.462400,240.462400,240.462400
XS GIS Cut Line= 6
789534.345300904823864.261666319789580.724216902823746.165061095
789613.511619552823701.299802443 789613.80273569823613.510664058
789621.262267642823560.425057403 789672.12308671823386.538647022
#Sta/Elev= 30
9845.207214.59289865.567207.68429886.708203.72179907.848198.13619929.231185.0007
9951.405173.29759959.032171.58399973.712166.42349989.668 155.1719995.557 152.411
   10001151.724510009.39152.228210024.44158.374210034.85 160.213 10074.9159.8485
 10084.9157.916610104.91158.813210114.91163.670110134.99177.823510145.09 183.293
10155.24191.7767 10165.4196.398610170.05197.123910185.97198.500410206.65198.0315
10257.13 199.74610300.64199.776710321.52200.946310331.97200.547110351.24204.3472
#Mann= 3 , 0 , 0
9845.207    0.04       09845.207    0.04       010351.24    0.04       0
#XS Ineff= 2 , 0
       0                               0
Bank Sta=9845.207,10351.24
Exp/Cntr=0.3,0.1

Type RM Length L Ch R = 1 ,13420.77,233.470800,233.470800,233.470800
XS GIS Cut Line= 6
789903.913451593823848.248612744789855.138117999823714.522303608
 789749.98300445823559.813200407789715.352577935823498.704399494
789702.210096232 823442.08371019789701.660851822823409.784374349
#Sta/Elev= 30
9696.303231.38499699.709 231.8689731.165218.48229741.651 214.5239762.622207.4973
9805.641191.20629827.418184.01329838.307179.35779861.197167.47889872.656162.5472
9880.071160.28529884.114 159.2829896.074158.81949908.134156.56679932.434156.1385
9957.462153.14689969.975153.37079982.489152.75479995.003149.069910000.55148.6993
10007.42149.331710019.76154.236510031.83156.657310035.59157.979510054.52 167.731
10078.55188.983210096.52199.966610100.43201.571410141.68200.8523 10187.1204.5474
#Mann= 3 , 0 , 0
9696.303  0.0946       09696.303  0.0946       0 10187.1  0.0946       0
#XS Ineff= 2 , 0
       0                               0
Bank Sta=9696.303,10187.1
Exp/Cntr=0.3,0.1

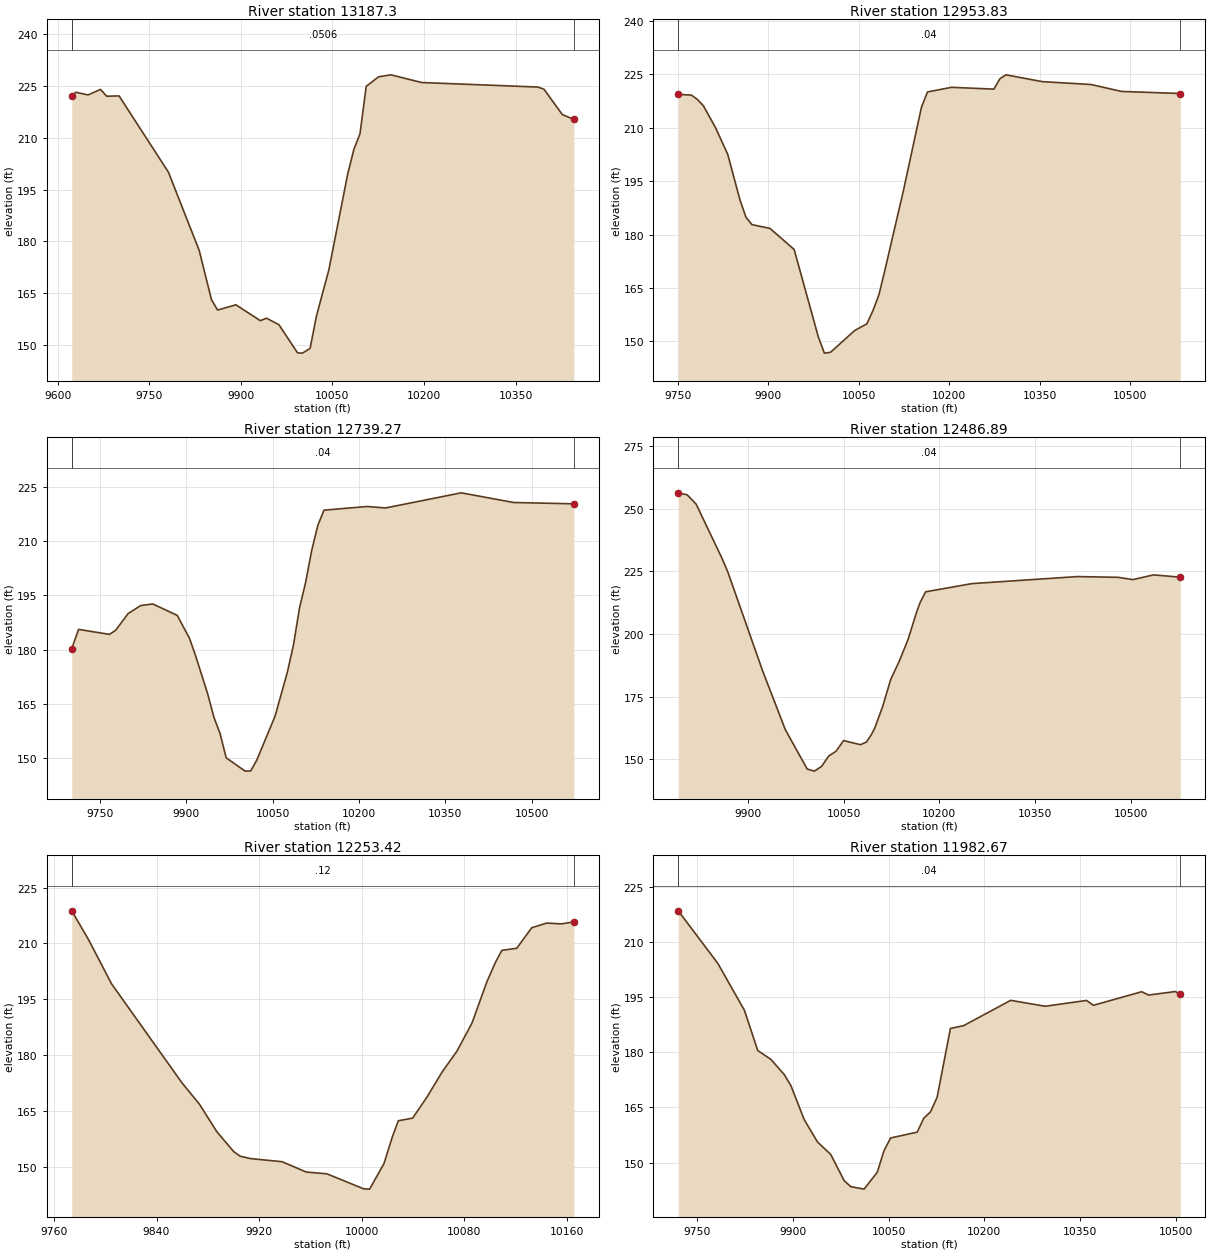
Type RM Length L Ch R = 1 , 13187.3,233.470900,233.470900,233.470900
XS GIS Cut Line= 6
789994.424996265823871.326668065789960.180443344823613.646130243
 789962.57577257823557.441661475789988.520885605823434.829550347
790010.118837489  823279.3547295790018.615297758823056.178916765
#Sta/Elev= 30
9623.256221.95959629.679223.15229649.982222.37589670.285223.97289680.436222.0058
9700.739222.09169781.583200.01879831.971177.38469852.012 163.1849862.033160.1463
9892.084161.6638 9932.12157.07369942.159157.79059962.422155.92629993.049147.7636
   10001147.687710013.61149.063610023.87158.351310044.39171.856910075.04199.3819
10085.18 206.56410095.32211.155410105.46224.859310125.74227.622310145.96228.1916
10196.29225.964710386.68224.653110396.68224.017110426.68216.691210445.51215.3018
#Mann= 3 , 0 , 0
9623.256  0.0506       09623.256  0.0506       010445.51  0.0506       0
#XS Ineff= 2 , 0
       0                               0
Bank Sta=9623.256,10445.51
Exp/Cntr=0.3,0.1

Type RM Length L Ch R = 1 ,12953.83,214.565300,214.565300,214.565300
XS GIS Cut Line= 6
790191.693482502823836.704070432790181.664511303823689.140614361
790206.524952181823401.946462276790206.731987363823315.585989253
790199.984364712823227.824738616790165.999805448823008.768515687
#Sta/Elev= 30
9750.828219.3596 9772.65219.16319782.704217.93559792.758216.11069812.866209.9425
9832.933202.51569852.943189.87819862.948184.94239872.954182.80159902.972181.7344
9943.021175.82279983.104151.26459993.155146.715810003.22146.937510043.48 153.073
10063.62154.943310073.69158.660410083.75163.202110093.82 170.24210123.99192.1866
10154.07215.730310164.09 220.04510204.15221.349910274.16220.838210284.18 223.757
10294.21224.855810354.39222.942810435.14222.137310485.69220.197610583.28219.6095
#Mann= 3 , 0 , 0
9750.828    0.04       09750.828    0.04       010583.28    0.04       0
#XS Ineff= 2 , 0
       0                               0
Bank Sta=9750.828,10583.28
Exp/Cntr=0.3,0.1

Type RM Length L Ch R = 1 ,12739.27,252.376400,252.376400,252.376400
XS GIS Cut Line= 6
790498.520887027823816.050415809790450.107649338823692.058683687
790351.057962383823414.074583388790268.808422987823193.203006383
790233.279805656823083.772860193790208.759290463822994.358121905
#Sta/Elev= 30
9701.475180.29549713.338185.59019767.014184.20749777.749185.35639799.219189.9528
9821.132192.18199842.083192.62059884.584189.46839905.834183.12879916.459178.3039
 9937.71167.62089948.335161.2433 9958.96156.76999969.585150.0753 10002.5 146.387
10012.08146.427310022.68149.431310054.49161.623310075.69173.6819 10086.3181.2057
 10096.9191.5411 10107.5198.5841 10118.1207.478210128.71 214.37110139.37218.5662
10214.07219.576510246.08219.173410377.71223.360110468.63220.680510573.15220.3201
#Mann= 3 , 0 , 0
9701.475    0.04       09701.475    0.04       010573.15    0.04       0
#XS Ineff= 2 , 0
       0                               0
Bank Sta=9701.475,10573.15
Exp/Cntr=0.3,0.1

Type RM Length L Ch R = 1 ,12486.89,233.470800,233.470800,233.470800
XS GIS Cut Line= 6
790775.115542958823547.810295381790681.081223298823466.059385415
790539.699834547823383.214434731790458.703857911823313.165399174
790340.895645458823146.237880054790271.197648301822974.928650153
#Sta/Elev= 30
9791.172256.3573 9805.29255.54849819.246251.83439859.914230.10429868.813224.7694
 9923.23185.35459958.834 161.8289993.102 146.11210004.39145.271410015.67147.1721
10026.94151.351410038.23153.193610050.05 157.457 10076.6155.8232 10085.9 156.901
10093.33159.755410098.57162.265710111.23171.0666 10123.9181.896110137.28189.1659
10151.02197.828110164.76209.0343 10169.9212.5644 10178.5216.840110251.08220.1245
10415.81222.9197 10479.7222.637610502.98221.712910535.49223.600910577.29222.6853
#Mann= 3 , 0 , 0
9791.172    0.04       09791.172    0.04       010577.29    0.04       0
#XS Ineff= 2 , 0
       0                               0
Bank Sta=9791.172,10577.29
Exp/Cntr=0.3,0.1

Type RM Length L Ch R = 1 ,12253.42,270.751800,270.751800,270.751800
XS GIS Cut Line= 6
790814.113592912823377.572490603790738.568192966823297.314360794
790701.226610528823249.885599199790690.281069937823231.155934551
790654.488791884823158.262013486790593.701643612823056.813887723
#Sta/Elev= 30
9773.871218.77139787.168210.90469804.871199.17469859.803172.57239873.537166.7804
9887.116159.39739900.184154.08339905.169152.83649913.251152.18319938.067151.3376
9956.836148.56759972.985148.082910001.64144.0549 10006.3143.972310017.49150.8264
10023.95157.911810028.68162.348310039.86163.0514 10051.2168.789410062.86175.4439
10074.52181.096210086.18188.601510097.84199.726310104.77205.119910109.49 208.141
10121.15208.719110132.81214.226410144.47215.475710156.12215.265610165.67215.7997
#Mann= 3 , 0 , 0
9773.871    0.12       09773.871    0.12       010165.67    0.12       0
#XS Ineff= 2 , 0
       0                               0
Bank Sta=9773.871,10165.67
Exp/Cntr=0.3,0.1

Type RM Length L Ch R = 1 ,11982.67,240.726000,240.726000,240.726000
XS GIS Cut Line= 3
 790838.97638914823364.632679358790979.923116028822881.198578715
791087.938364685822619.064011887
#Sta/Elev= 30
9720.381 218.5299782.496204.20889824.162191.44579844.994180.51689865.827 178.061
 9886.66173.93459897.076170.91769917.909161.67949938.741155.60589959.574152.1769
9980.407145.11329990.823143.444610011.66  142.7710032.49 147.392 10042.9153.2178
10053.32156.698510094.99158.2786 10105.4162.090910115.82163.794310126.24167.7778
10147.07 186.517 10167.9187.276810241.46194.161810295.54192.554210360.44194.1271
10371.25192.813210446.96196.506710457.78195.600610499.75 196.56110507.46195.8129
#Mann= 3 , 0 , 0
9720.381    0.04       09720.381    0.04       010507.46    0.04       0
#XS Ineff= 2 , 0
       0                               0
Bank Sta=9720.381,10507.46
Exp/Cntr=0.3,0.1

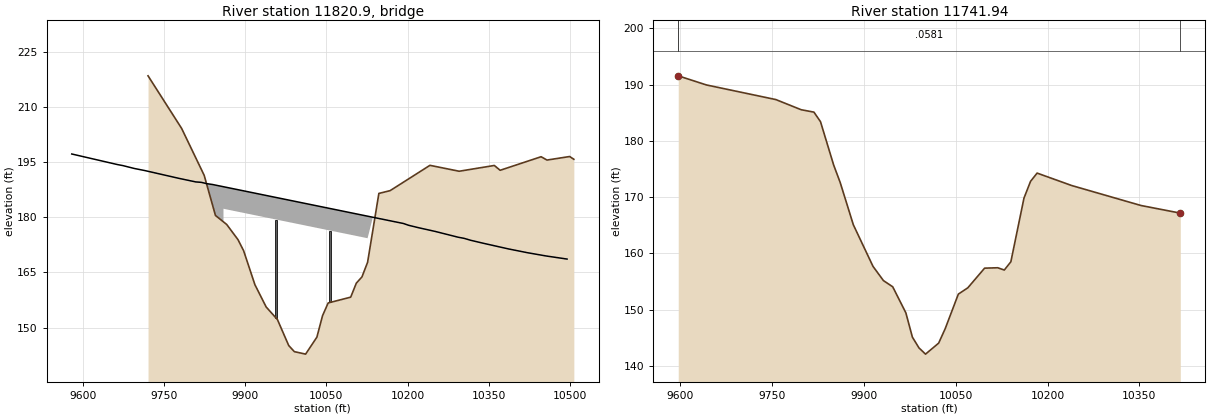
Type RM Length L Ch R = 3 , 11820.9,,,
BEGIN DESCRIPTION:
END DESCRIPTION:
Bridge Culvert--1,0,-1,-1, 0
Deck Dist Width WeirC Skew NumUp NumDn MinLoCord MaxHiCord MaxSubmerge Is_Ogee
90.863000,59.000000,2.6,0, 26, 25, , , 0.95, 0, 0,0,,
 9579.41 9663.60 9673.95 9694.65 9714.45 9777.45 9808.51 9818.86 9829.21 9839.50
 9859.84 9859.8410154.8410154.8410192.4710201.8310219.6310251.2010293.1910304.86
10316.5410339.8010386.5910421.6210456.6410494.90
  197.25  194.38  194.09  193.32  192.74  190.62  189.65  189.53  189.17  188.95
  188.34  188.34  179.46  179.46  178.33  177.85  177.21  176.17  174.61  174.28
  173.77  172.96  171.41  170.38  169.48  168.65
 -802.75 -805.62 -805.91 -806.68 -807.26 -809.38 -810.35 -810.47 -810.83 -811.05
 -811.66  182.34  173.46 -820.54 -821.67 -822.15 -822.79 -823.83 -825.39 -825.72
 -826.23 -827.04 -828.59 -829.62 -830.52 -831.35
 9579.41 9663.60 9673.95 9694.65 9714.45 9767.10 9808.51 9818.86 9829.21 9841.59
 9841.5910136.5910136.5910192.4710201.8310219.6310251.2010293.1910304.8610316.54
10339.8010386.5910421.6210456.6410494.90
  197.25  194.38  194.09  193.32  192.74  190.95  189.65  189.53  189.17  188.89
  188.89  180.01  180.01  178.33  177.85  177.21  176.17  174.61  174.28  173.77
  172.96  171.41  170.38  169.48  168.65
 -802.75 -805.62 -805.91 -806.68 -807.26 -809.05 -810.35 -810.47 -810.83 -811.11
  182.89  174.01 -819.99 -821.67 -822.15 -822.79 -823.83 -825.39 -825.72 -826.23
 -827.04 -828.59 -829.62 -830.52 -831.35
Pier Skew, UpSta & Num, DnSta & Num=  ,9957.51, 2 ,9939.26, 2 , 0 , 0 , 0 ,,
    4.00    4.00
 -814.60  185.40
    4.00    4.00
 -814.05  185.95
Pier Skew, UpSta & Num, DnSta & Num=  ,10057.17, 2 ,10038.93, 2 , 0 , 0 , 0 ,,
    4.00    4.00
 -817.60  182.40
    4.00    4.00
 -817.05  182.95
BR Coef=-1 , 0 , 0 ,, 0 ,,,0.8,0,1,0,
WSPro=,,,, 1 ,,,, 0 ,,,, 0 ,,,,-1 ,-1 ,-1 , 0 , 0 , 0 , 0 , 0
BC Design=,, 0 ,, 0 ,,,,,,

Type RM Length L Ch R = 1 ,11741.94,57.175400,57.175400,57.175400
XS GIS Cut Line= 4
791018.123630792823389.660602838791070.813995987823182.850919411
791206.491686344822833.777250051791315.824194133822628.284825787
#Sta/Elev= 30
9596.374191.56289642.462189.94049755.976187.34149797.254185.54069818.214185.1077
9828.943183.4088  9850.4 175.7229861.129172.60049882.587165.09399914.773157.6951
9931.758 155.1749946.959154.06769968.417149.45189979.146145.12069989.875143.2105
 10000.6142.101210022.06144.056910032.79146.633310054.25152.765710069.77153.8894
10097.16157.379810118.62157.451110129.35157.046910140.08158.513910161.54169.8348
10172.26172.806710182.99174.275310239.56172.063910352.83168.514510417.07 167.161
#Mann= 3 , 0 , 0
9596.374  0.0581       09596.374  0.0581       010417.07  0.0581       0
#XS Ineff= 2 , 0
       0                               0
Bank Sta=9596.374,10417.07
Exp/Cntr=0.3,0.1