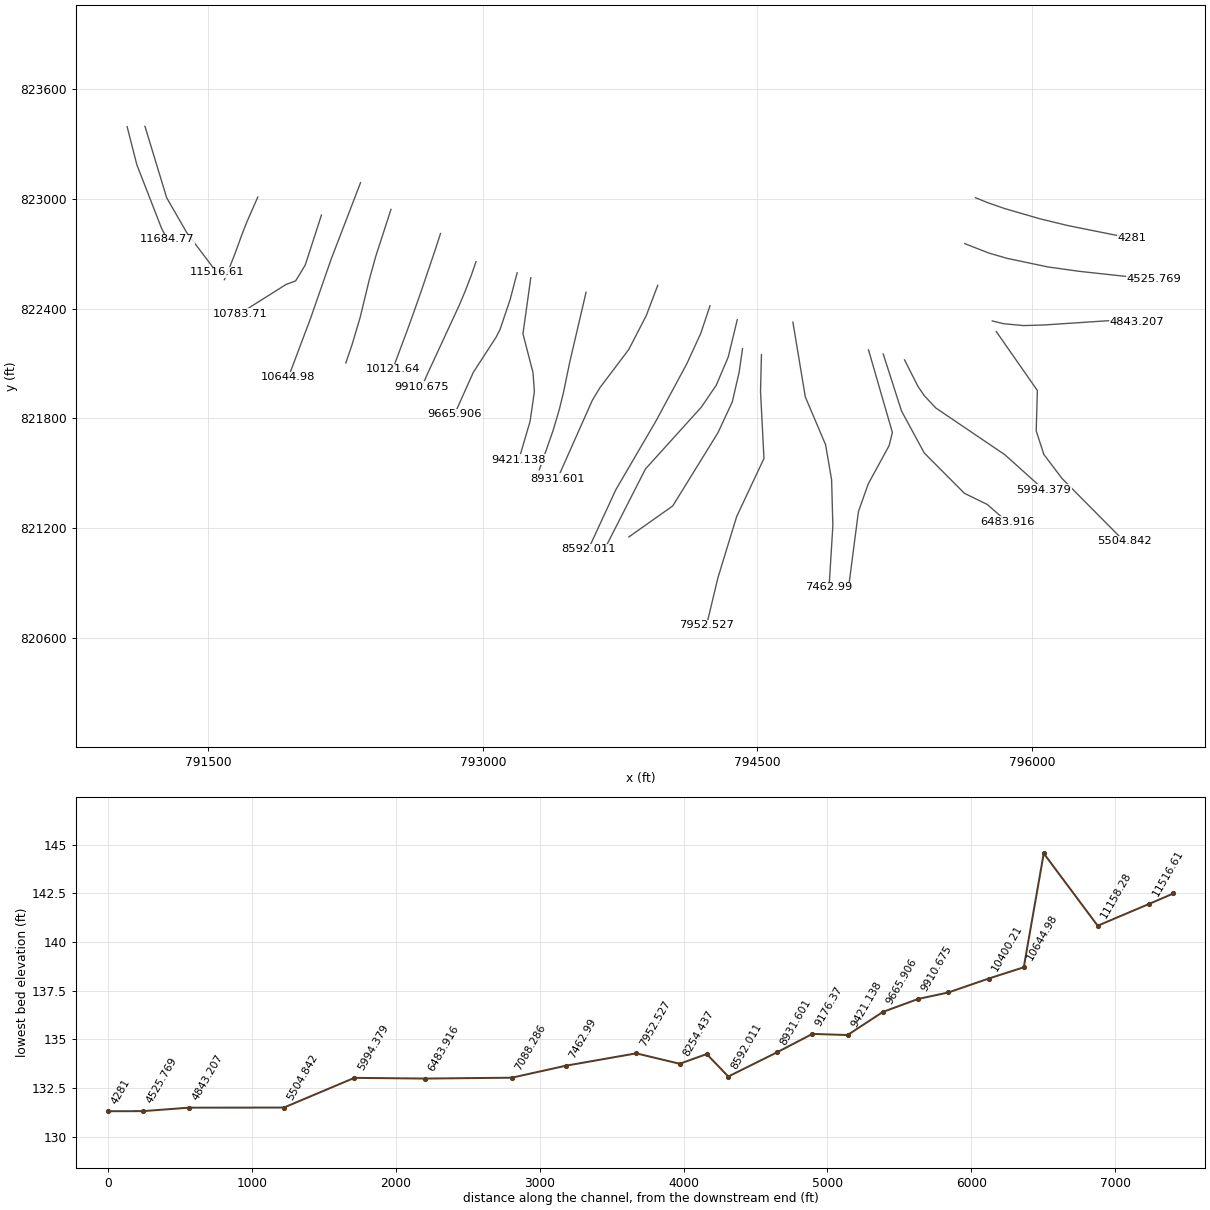
HEC-RAS study 18193_ras.prj: 18193

--- 18193_ras.g01 (geometry) --- (continued)

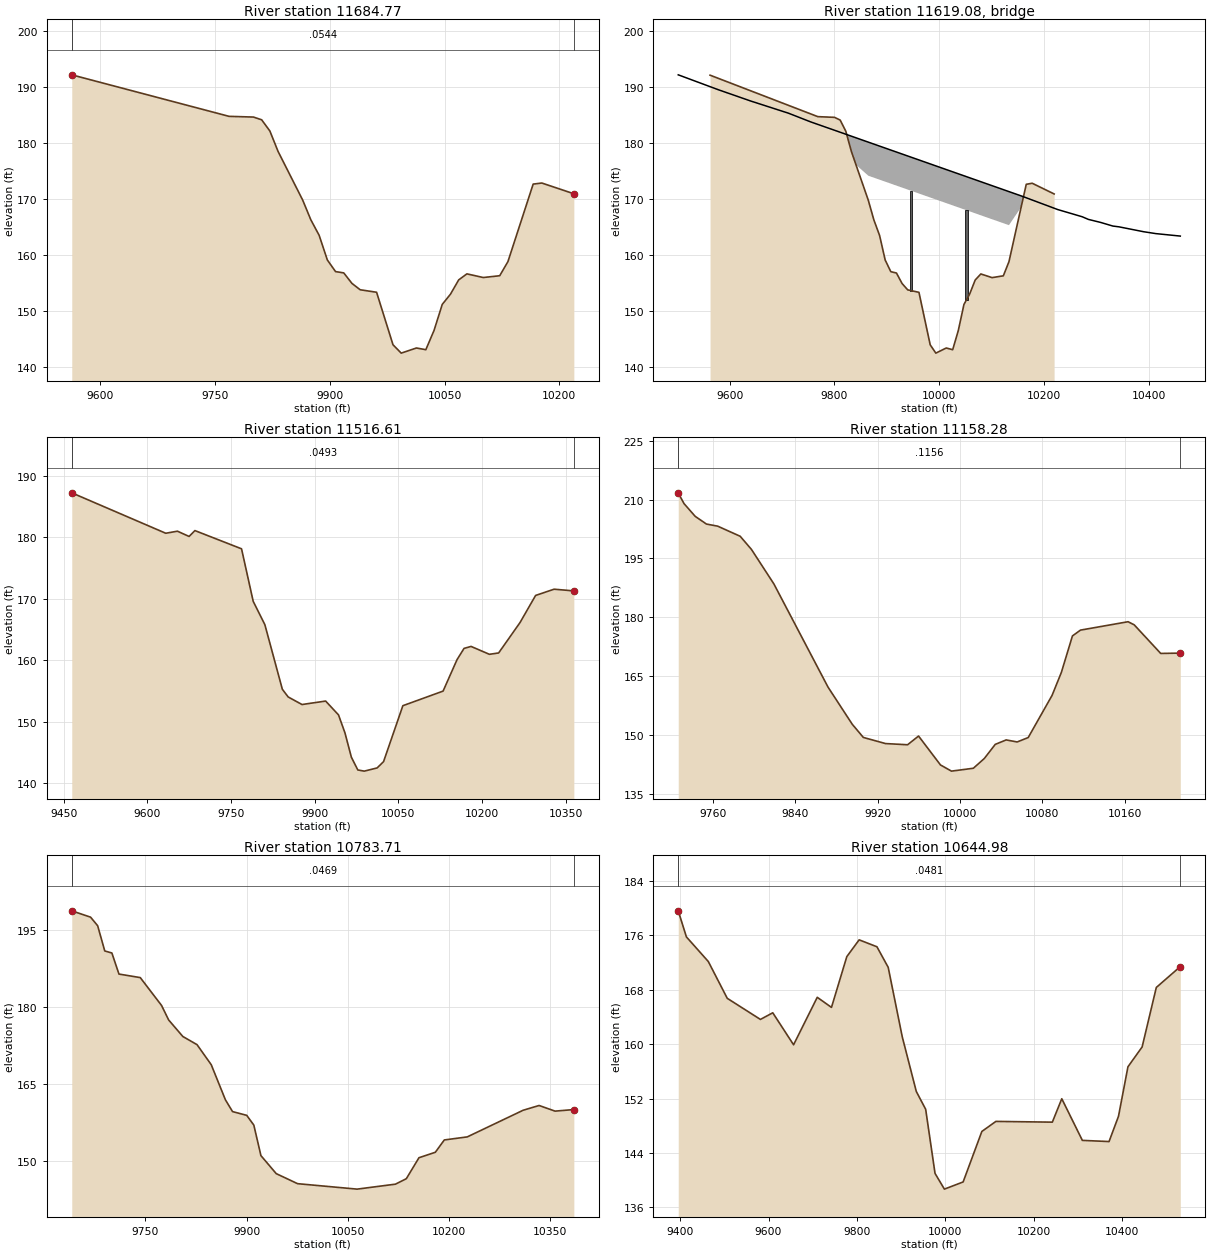
Type RM Length L Ch R = 1 ,11684.77,168.152900,168.152900,168.152900
XS GIS Cut Line= 4
791056.445652828823394.208677624791109.136018023823187.398994196
 791244.81370838822838.325324837791276.869554621822778.075782508
#Sta/Elev= 30
9562.749192.14789768.322 184.7389800.197184.61119810.926184.12369821.655182.1261
9832.384178.4773 9864.57169.78929875.162166.28669886.028163.51939896.756159.1138
9907.485157.03779918.214156.80179928.943154.92959939.672153.79279961.129153.3488
9982.587143.97799993.316142.487110013.18143.4018 10025.5143.100110036.23146.5404
10046.96151.185610057.69153.005410068.42155.551110079.15156.6321 10100.6155.9769
10122.06156.299310132.79158.817710165.77172.6487 10177.1172.840110218.93170.9267
#Mann= 3 , 0 , 0
9562.749  0.0544       09562.749  0.0544       010218.93  0.0544       0
#XS Ineff= 2 , 0
       0                               0
Bank Sta=9562.749,10218.93
Exp/Cntr=0.3,0.1

Type RM Length L Ch R = 3 ,11619.08,,,
BEGIN DESCRIPTION:
END DESCRIPTION:
Bridge Culvert--1,0,-1,-1, 0
Deck Dist Width WeirC Skew NumUp NumDn MinLoCord MaxHiCord MaxSubmerge Is_Ogee
54.576450,59.000000,2.6,0, 18, 20, , , 0.95, 0, 0,0,,
 9502.05 9578.43 9640.27 9712.42 9754.37 9841.06 9841.0610156.0610156.0610225.77
10272.5510284.2410307.6310331.0210342.7210389.4910412.8810459.59
  192.21  189.55  187.53  185.35  183.81  180.96  180.96  170.58  170.58  168.14
  166.85  166.38  165.84  165.19  165.05  164.18  163.84  163.40
 -807.79 -810.45 -812.47 -814.65 -816.19 -819.04  174.96  164.58 -829.42 -831.86
 -833.15 -833.62 -834.16 -834.81 -834.95 -835.82 -836.16 -836.60
 9502.05 9578.43 9640.27 9722.73 9754.37 9800.91 9800.9110115.9110115.9110159.24
10225.7710272.5510284.2410307.6310319.3310331.0210342.7210390.7610412.8810459.59
  192.21  189.55  187.53  185.01  183.81  182.28  182.28  171.90  171.90  170.48
  168.14  166.85  166.38  165.84  165.47  165.19  165.05  164.16  163.84  163.40
 -807.79 -810.45 -812.47 -814.99 -816.19 -817.72  176.28  165.90 -828.10 -829.52
 -831.86 -833.15 -833.62 -834.16 -834.53 -834.81 -834.95 -835.84 -836.16 -836.60
Pier Skew, UpSta & Num, DnSta & Num=  ,9945.39, 2 ,9905.24, 2 , 0 , 0 , 0 ,,
    4.00    4.00
 -822.48  177.52
    4.00    4.00
 -821.16  178.84
Pier Skew, UpSta & Num, DnSta & Num=  ,10051.73, 2 ,10011.57, 2 , 0 , 0 , 0 ,,
    4.00    4.00
 -825.98  174.02
    4.00    4.00
 -824.66  175.34
BR Coef=-1 , 0 , 0 ,, 0 ,,,0.8,0,1,0,
WSPro=,,,, 1 ,,,, 0 ,,,, 0 ,,,,-1 ,-1 ,-1 , 0 , 0 , 0 , 0 , 0
BC Design=,, 0 ,, 0 ,,,,,,

Type RM Length L Ch R = 1 ,11516.61,358.328700,358.328700,358.328700
XS GIS Cut Line= 4
791153.801321179823396.246898457791272.354642838823006.338196024
 791383.00440976822814.018363088791546.344541848822597.987865806
#Sta/Elev= 30
9464.402187.22589632.938180.64929653.842180.98539674.776180.12959685.198181.0839
9768.815178.11819789.719169.57549810.623165.78589841.979155.26939852.431154.0172
9877.241152.78749919.628153.35059942.702151.09729954.239148.17619965.776144.2149
9977.313142.1403 9988.85141.952610011.92142.472510023.46143.495810058.07152.5963
10130.19154.971310155.27160.0969 10167.8161.918210180.34162.239410213.19160.9566
10229.77161.1736 10268.1166.114310296.09170.533610329.25 171.54810364.65171.2708
#Mann= 3 , 0 , 0
9464.402  0.0493       09464.402  0.0493       010364.65  0.0493       0
#XS Ineff= 2 , 0
       0                               0
Bank Sta=9464.402,10364.65
Exp/Cntr=0.3,0.1

Type RM Length L Ch R = 1 ,11158.28,374.576300,374.576300,374.576300
XS GIS Cut Line= 6
791770.325926953823010.085622408791711.940315629822876.873609885
791686.856231975822813.828274104791647.499113464822705.481774573
791620.902532174822637.234624707791587.604951229822558.290673424
#Sta/Elev= 30
9726.369211.72549731.922209.0005 9742.84205.73449753.758203.77079764.677203.2323
9786.513200.65969797.432197.31969819.268188.50989871.814  162.239895.356152.7645
9906.118149.41199927.643147.84979949.065147.5471 9959.71149.76829981.002142.4073
9991.647140.830310012.92141.560810023.55144.042410034.19147.648410044.82  148.78
10055.46148.259210066.19149.385410089.36160.124510098.39165.988110109.12175.2625
 10116.9176.749210163.17178.889410169.11178.095510194.84 170.81210213.87170.8907
#Mann= 3 , 0 , 0
9726.369  0.1156       09726.369  0.1156       010213.87  0.1156       0
#XS Ineff= 2 , 0
       0                               0
Bank Sta=9726.369,10213.87
Exp/Cntr=0.3,0.1

Type RM Length L Ch R = 1 ,10783.71,138.727200,138.727200,138.727200
XS GIS Cut Line= 5
792118.035004139822911.495538697792029.778642446 822638.82289882
 791977.08827728822551.883796275791924.397912055822532.124909312
791671.484159172822372.736554623
#Sta/Elev= 30
9641.175198.69079669.024 197.4599679.534195.78739690.045190.87819700.556190.4892
9711.067186.38559742.599185.70119774.131180.28179784.642177.45729805.664174.2382
9826.685 172.6539847.707168.74789868.728161.91489879.239159.63169900.261158.8972
9910.771 157.0029921.282151.06469943.938147.55899975.582145.6029 10063.7144.5432
10120.46145.507510136.58146.571310155.34150.655510179.56151.716910192.85154.1104
10226.84154.705310309.58 159.88910333.22160.816510356.86 159.71910384.66160.0225
#Mann= 3 , 0 , 0
9641.175  0.0469       09641.175  0.0469       010384.66  0.0469       0
#XS Ineff= 2 , 0
       0                10091.55       0
Bank Sta=9641.175,10384.66
Exp/Cntr=0.3,0.1

Type RM Length L Ch R = 1 ,10644.98,244.768500,244.768500,244.768500
XS GIS Cut Line= 6
792331.615393306823088.443262094792170.581430763822669.070494531
792119.957382092822523.746334028792119.342521126822521.843192942
792059.725854058822350.338227555791936.995512587822024.205103457
#Sta/Elev= 30
9395.883179.61649414.338175.78559463.843172.1675 9506.69166.75449581.716163.6479
9609.613164.62569656.657 159.9229710.216166.90089742.352165.41769776.992172.8781
9804.888175.35039845.111174.3322  9870.6171.30989902.368161.09529934.136153.0537
9955.315150.43849976.494141.00649997.672 138.69710040.01139.751510082.35147.1764
10114.11148.6548 10241.7148.544810263.07151.986210309.56145.863710369.91 145.691
10391.28149.410610412.65156.685510444.71159.599310476.76168.347410531.03171.4202
#Mann= 3 , 0 , 0
9395.883  0.0481       09395.883  0.0481       010531.03  0.0481       0
#XS Ineff= 2 , 0
       0                10098.74       0
Bank Sta=9395.883,10531.03
Exp/Cntr=0.3,0.1

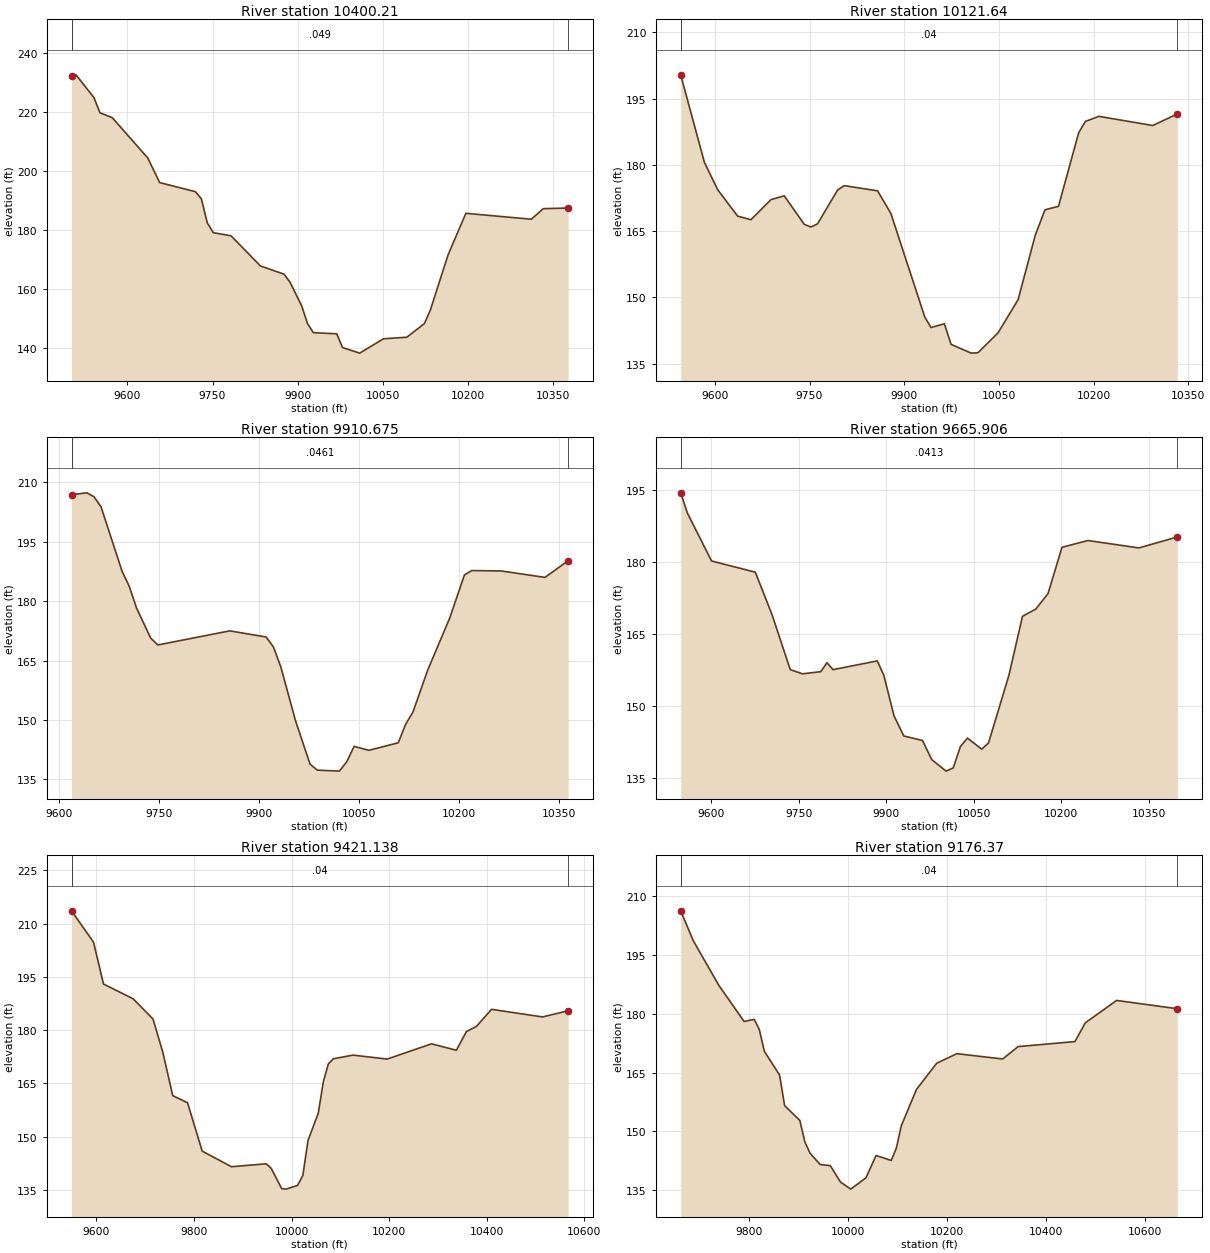
Type RM Length L Ch R = 1 ,10400.21,278.575000,278.575000,278.575000
XS GIS Cut Line= 6
792497.959953248822942.535723144792414.134567615 822683.66724123
792379.540051904 822558.60749519792329.383077428822351.468244046
792286.281659088822206.395703635792251.253768551 822103.53706952
#Sta/Elev= 30
9501.575232.16219509.528232.72659541.191224.96659551.745219.81879573.366218.1605
 9635.95204.46089656.926 196.0949719.852193.0002 9730.34190.60479740.828182.3866
9751.315179.07739782.681 177.9919834.559167.74119876.061164.95159886.437162.2665
9907.153154.15889917.433148.14079927.712145.0701 9968.83144.68889979.109140.0056
10009.31138.115710051.15142.986810092.34143.525310123.32 148.16310133.75152.7411
10165.05171.546410196.34185.648710311.64183.639310332.77187.231810376.57187.4418
#Mann= 3 , 0 , 0
9501.575   0.049       09501.575   0.049       010376.57   0.049       0
#XS Ineff= 2 , 0
       0                               0
Bank Sta=9501.575,10376.57
Exp/Cntr=0.3,0.1

Type RM Length L Ch R = 1 ,10121.64,210.961900,210.961900,210.961900
XS GIS Cut Line= 6
792768.546825843822810.830951247792740.296462912822723.280707212
792660.790290429822489.153934301792622.353273869822380.103232535
792586.034948776822279.332919292792507.233855803822068.552578021
#Sta/Elev= 30
9545.848200.35759583.499180.53829604.514174.37069636.037168.4008 9657.15167.5779
9688.832172.12889709.954172.98919741.637 166.5519752.197165.91789762.758166.6621
9794.441174.28789805.002175.29189857.806174.11789878.928169.00569932.602145.5845
9942.521143.19349963.727144.0461 9974.33139.378510006.15137.405210016.78137.4875
10048.67141.972210080.56149.504910107.84164.144410123.15169.8238 10144.5170.6067
10176.53187.2595 10187.2189.822410208.55190.962910293.96188.895110332.87191.5131
#Mann= 3 , 0 , 0
9545.848    0.04       09545.848    0.04       010332.87    0.04       0
#XS Ineff= 2 , 0
       09871.835                       0
Bank Sta=9545.848,10332.87
Exp/Cntr=0.3,0.1

Type RM Length L Ch R = 1 ,9910.675,244.768500,244.768500,244.768500
XS GIS Cut Line= 6
792962.550908916822656.843207317792936.267089756822580.675903121
792901.932982776 822492.03071227 792871.73529305822420.494768485
792695.586897601822039.946567187792666.679617083821973.066805978
#Sta/Elev= 30
9618.527206.89499641.634207.37749652.213206.40619662.791203.86769694.527187.5212
9705.189183.77569715.912178.3667 9737.36170.68439748.084168.94089856.068172.5032
9910.739170.95669921.706168.40959932.673163.43459954.606149.8955 9976.54138.8443
9987.544137.321110020.66137.0707 10031.7139.441810042.74143.332210064.82142.3224
10108.97144.233810120.01148.887510131.05151.987610153.12162.570110186.24175.7432
10208.31186.634110219.35187.7391 10263.5187.637110329.23186.013810364.02 190.224
#Mann= 3 , 0 , 0
9618.527  0.0461       09618.527  0.0461       010364.02  0.0461       0
#XS Ineff= 2 , 0
       0                               0
Bank Sta=9618.527,10364.02
Exp/Cntr=0.3,0.1

Type RM Length L Ch R = 1 ,9665.906,244.768500,244.768500,244.768500
XS GIS Cut Line= 6
793187.280001496822596.166352325793149.110300303822449.983031408
793093.849699721822286.519306887793071.967509974 822243.57566636
792947.799368448822052.071486301792845.533253763821823.872315089
#Sta/Elev= 30
9548.078 194.4669559.618190.23269600.959180.24779675.849177.90919704.375169.1013
9735.762157.58049756.687156.70219788.074157.15949798.536159.01899808.998157.5798
9884.769159.39759895.993156.39239913.359147.94729930.162 143.739 9962.16142.7952
9978.006138.812210002.59136.4038 10014.8137.074810027.01141.508310039.22143.2954
10063.64140.978610075.28142.292710110.19156.403210133.42168.706410156.33170.2234
10177.11173.430710201.03183.098410245.44184.516910332.85182.968410398.63185.2597
#Mann= 3 , 0 , 0
9548.078  0.0413       09548.078  0.0413       010398.63  0.0413       0
#XS Ineff= 2 , 0
       0                               0
Bank Sta=9548.078,10398.63
Exp/Cntr=0.3,0.1

Type RM Length L Ch R = 1 ,9421.138,244.768500,244.768500,244.768500
XS GIS Cut Line= 6
793261.901845681 822569.20896755793219.025745046822262.802729375
793273.902366606822050.883465818793281.543277831  821947.2033995
793258.102488073 821784.82771934793196.504780305821575.146675286
#Sta/Elev= 30
9549.206213.60239594.364204.77189614.734192.99219675.812188.79879716.223183.1159
9736.428173.69279756.634161.54659786.855159.55779816.949145.92959876.989141.5296
9948.158142.35089958.489141.05119979.901135.33989988.716135.219610012.35136.2736
10023.17139.086910033.73148.945810054.74 156.60410065.04165.395410075.34170.4786
10085.53171.937310125.89172.960710195.99171.847810286.63176.141410337.64174.3323
10358.16 179.585 10378.8181.061210409.75185.857110514.14183.715110566.65185.4666
#Mann= 3 , 0 , 0
9549.206    0.04       09549.206    0.04       010566.65    0.04       0
#XS Ineff= 2 , 0
       0                               0
Bank Sta=9549.206,10566.65
Exp/Cntr=0.3,0.1

Type RM Length L Ch R = 1 , 9176.37,244.768400,244.768400,244.768400
XS GIS Cut Line= 6
   793563.837128822489.937053206793475.463768366822111.350192915
793440.109201392821940.678494964793417.932718538821850.438581422
793383.425127706821733.383254965793308.261374925821519.659135303
#Sta/Elev= 30
9661.251206.30589686.886198.64039738.261187.31489789.502178.06749809.999178.6044
9820.247176.02329830.496170.45569861.241164.40889871.489156.58029902.234152.8138
9912.482147.30959922.731144.48399943.243141.56149963.847141.2703 9984.45137.0881
10005.06135.275810035.97 138.15710056.52143.862610087.16142.594910097.37145.7184
10107.58151.473210138.22160.729210179.07 167.40410219.92169.844310312.56168.4914
10343.78171.653810458.68172.933210479.78177.727510543.07183.436910665.87181.3176
#Mann= 3 , 0 , 0
9661.251    0.04       09661.251    0.04       010665.87    0.04       0
#XS Ineff= 2 , 0
       0                               0
Bank Sta=9661.251,10665.87
Exp/Cntr=0.3,0.1

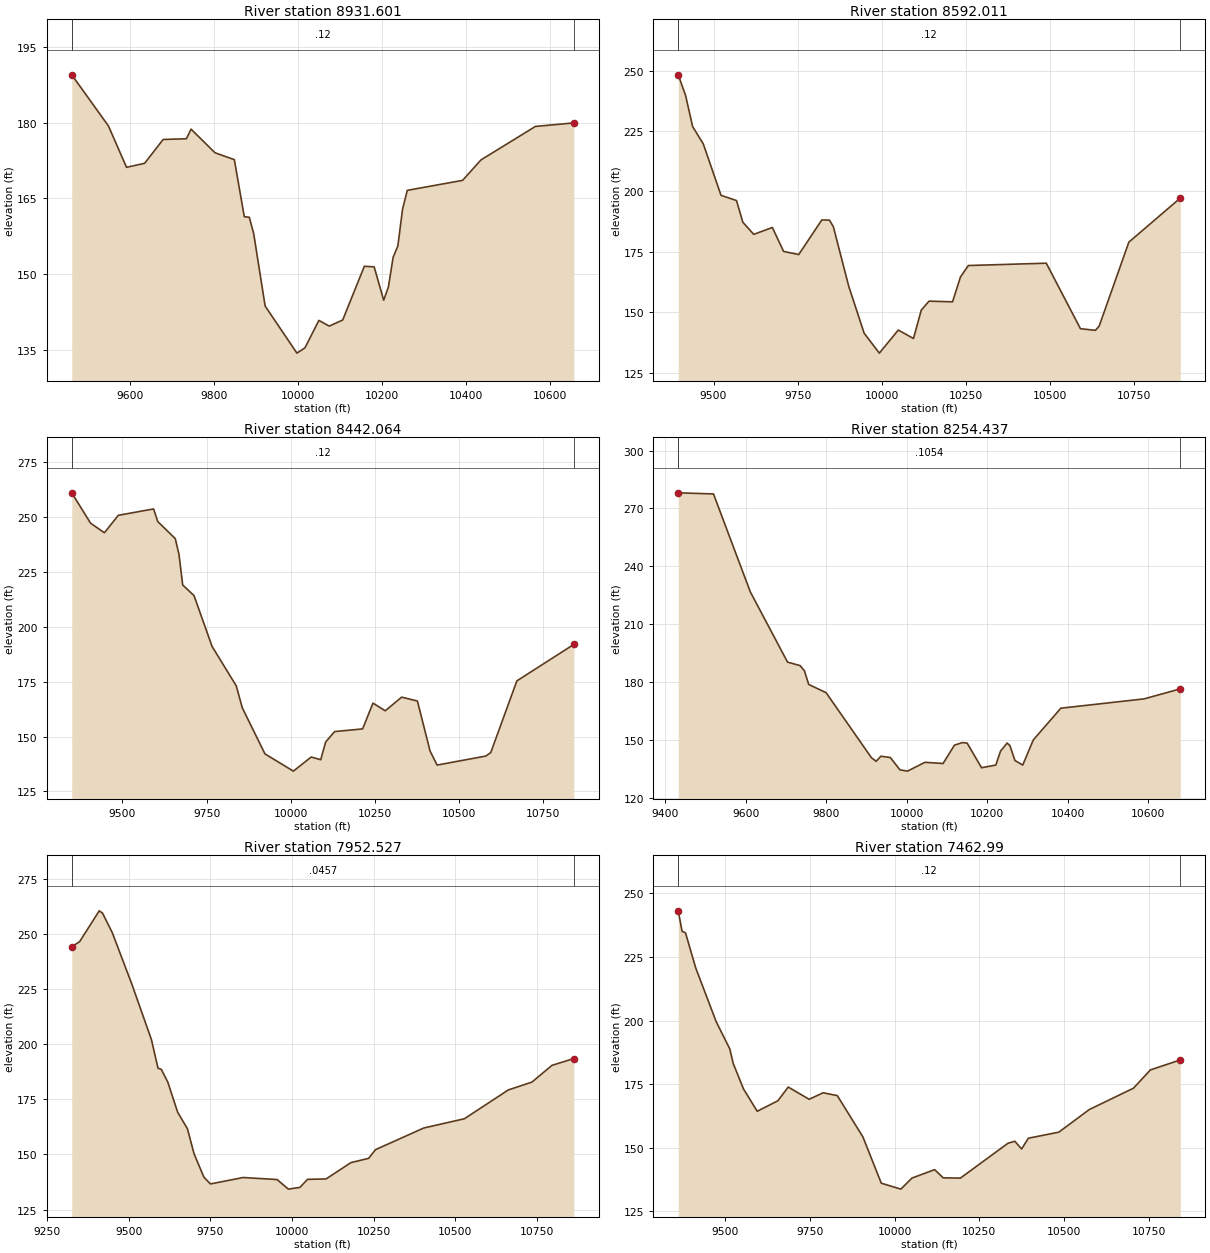
Type RM Length L Ch R = 1 ,8931.601,339.590300,339.590300,339.590300
XS GIS Cut Line= 6
793955.494966664822527.317680424793893.019862088822362.775680577
793797.279867145822177.185149844793640.290368322821969.117371964
793598.288694913821899.955736743793407.380755004821470.446016526
#Sta/Elev= 30
9460.101189.52479547.593179.37789590.681171.1811 9633.77171.97649677.959176.7053
9733.448176.85059744.532178.75379801.699174.06589847.714172.7084 9871.51161.3859
9883.407161.28219893.894158.03039921.183143.67539996.945134.335910016.12135.3879
10049.37140.824810074.09139.695410106.09140.901710157.71151.5592 10181.1151.4452
10203.84144.829210215.09147.462510226.35153.3364 10237.6155.578810248.86162.8879
10260.11166.614810392.04168.598310435.69172.644310565.66179.291110657.25179.9887
#Mann= 3 , 0 , 0
9460.101    0.12       09460.101    0.12       010657.25    0.12       0
#XS Ineff= 2 , 0
       0                               0
Bank Sta=9460.101,10657.25
Exp/Cntr=0.3,0.1

Type RM Length L Ch R = 1 ,8592.011,149.946700,149.946700,149.946700
XS GIS Cut Line= 6
794241.127387495822415.851369857794190.781604597822265.886529675
794114.575370626822099.495589137793943.109562004821781.598560688
793726.897203014 821411.64035409793576.086061346821084.820794143
#Sta/Elev= 30
9395.238248.25779417.123239.68839438.115226.81529469.603219.68279522.378 198.391
9568.308 196.2329587.007187.28039619.582182.23769674.782185.08189708.167175.1782
9753.112173.88639821.675188.21319844.529188.12059855.956185.39589901.664160.7455
9947.372  141.34 9992.55133.088910048.84 142.64110093.94139.142310116.92150.8293
   10140154.601610209.96154.326710233.42164.578310256.88169.340410488.36170.3058
10589.85143.190810634.34142.521410645.37144.2581 10733.6179.023510886.41197.2483
#Mann= 3 , 0 , 0
9395.238    0.12       09395.238    0.12       010886.41    0.12       0
#XS Ineff= 2 , 0
       0                10325.09       0
Bank Sta=9395.238,10886.41
Exp/Cntr=0.3,0.1

Type RM Length L Ch R = 1 ,8442.064,187.626900,187.626900,187.626900
XS GIS Cut Line= 6
794390.024023439822339.896715323794340.480826156 822135.42142835
794275.504213323821982.413977705794193.853853909821862.343778451
793888.117829728821523.893763608793657.096100576821070.091696093
#Sta/Elev= 30
9349.411261.1321 9405.23247.29919446.347 242.9269487.598250.87889592.409253.7916
9604.792248.01369656.808240.24059667.707233.11889678.843219.09949712.359214.2914
9766.127191.07869837.834173.12239855.683163.13649923.011142.116110007.47 134.243
10060.45 140.67810088.64139.449510103.29147.5346 10129.9152.273610213.11153.4969
10243.79165.249810280.29161.747310328.95167.9765 10375.8166.203110413.38143.3755
10434.29137.002710578.87 141.11510593.53142.691310671.08175.383810840.27192.0274
#Mann= 3 , 0 , 0
9349.411    0.12       09349.411    0.12       010840.27    0.12       0
#XS Ineff= 2 , 0
       0                10322.96       0
Bank Sta=9349.411,10840.27
Exp/Cntr=0.3,0.1

Type RM Length L Ch R = 1 ,8254.437,301.910000,301.910000,301.910000
XS GIS Cut Line= 6
794418.807062119822181.632557586794400.204755545822052.742616042
794362.728808582821890.695420638794284.663529873821722.626132935
794037.679718047821322.483627096793797.837840229821152.930319205
#Sta/Elev= 30
9432.818278.10649520.348277.52789611.783226.72069704.215190.29229735.507188.4725
9746.116 185.7859756.725178.72399799.944174.42999912.466140.70539924.183138.8197
9935.977141.48859959.566140.78559983.154134.417110002.06133.744310045.34138.3185
10090.35137.709410118.53147.203610138.11 148.55510150.05148.297710185.88135.5037
10221.26136.890310232.92144.085310249.33 148.31410256.25146.999910268.74139.2691
10288.16136.907410314.33 149.92910382.73166.391310589.12171.212410679.32176.4139
#Mann= 3 , 0 , 0
9432.818  0.1054       09432.818  0.1054       010679.32  0.1054       0
#XS Ineff= 2 , 0
       0                               0
Bank Sta=9432.818,10679.32
Exp/Cntr=0.3,0.1

Type RM Length L Ch R = 1 ,7952.527,489.537000,489.537000,489.537000
XS GIS Cut Line= 6
794522.098988712822149.073069002794517.065728914821948.090999598
794535.866486407 821581.81378294794386.797185747821264.547660639
794284.279199384820929.761289131794222.137847993820669.737438621
#Sta/Elev= 30
9325.656244.21079349.745246.55449409.776260.53029419.778259.52269449.784250.6087
9509.795 227.2359569.819 202.0329589.829189.10719599.833188.63079619.843182.8195
9649.904  169.219680.032161.63379700.117150.36519730.244139.75269750.329136.6277
9850.629139.54779954.499 138.6269989.251134.278710024.45135.059110047.84 138.714
10104.44138.894610180.93146.3229 10234.7148.221810255.99 152.17410403.43161.9886
10528.27166.208910662.92179.284210735.11182.8376 10796.7190.446410863.52193.5128
#Mann= 3 , 0 , 0
9325.656  0.0457       09325.656  0.0457       010863.52  0.0457       0
#XS Ineff= 2 , 0
       0                               0
Bank Sta=9325.656,10863.52
Exp/Cntr=0.3,0.1

Type RM Length L Ch R = 1 , 7462.99,374.703900,374.703900,374.703900
XS GIS Cut Line= 6
794693.943547339822326.297410017794761.883266326821917.582906447
794872.599147166821656.451412683 794905.40436133821465.024686199
794912.261243477821213.382995582794891.357175069820876.997150558
#Sta/Elev= 30
9360.904243.16649372.282235.11489382.353234.51649412.566220.68239472.992199.5435
9513.276188.7964 9523.36183.06749553.699173.0668 9594.15164.28819655.113168.4075
9685.774173.81729747.479169.00059788.833171.56229830.659170.45069906.257 154.199
9960.562135.977610018.32133.6434 10051.1137.994710118.05141.316210143.52138.0861
10194.08 137.97610334.89151.707610354.91152.483510374.93149.442110394.93153.6761
10484.94156.070610575.03164.984210705.28173.367210755.39180.5764 10843.6184.4874
#Mann= 3 , 0 , 0
9360.904    0.12       09360.904    0.12       0 10843.6    0.12       0
#XS Ineff= 2 , 0
       0                               0
Bank Sta=9360.904,10843.6
Exp/Cntr=0.3,0.1

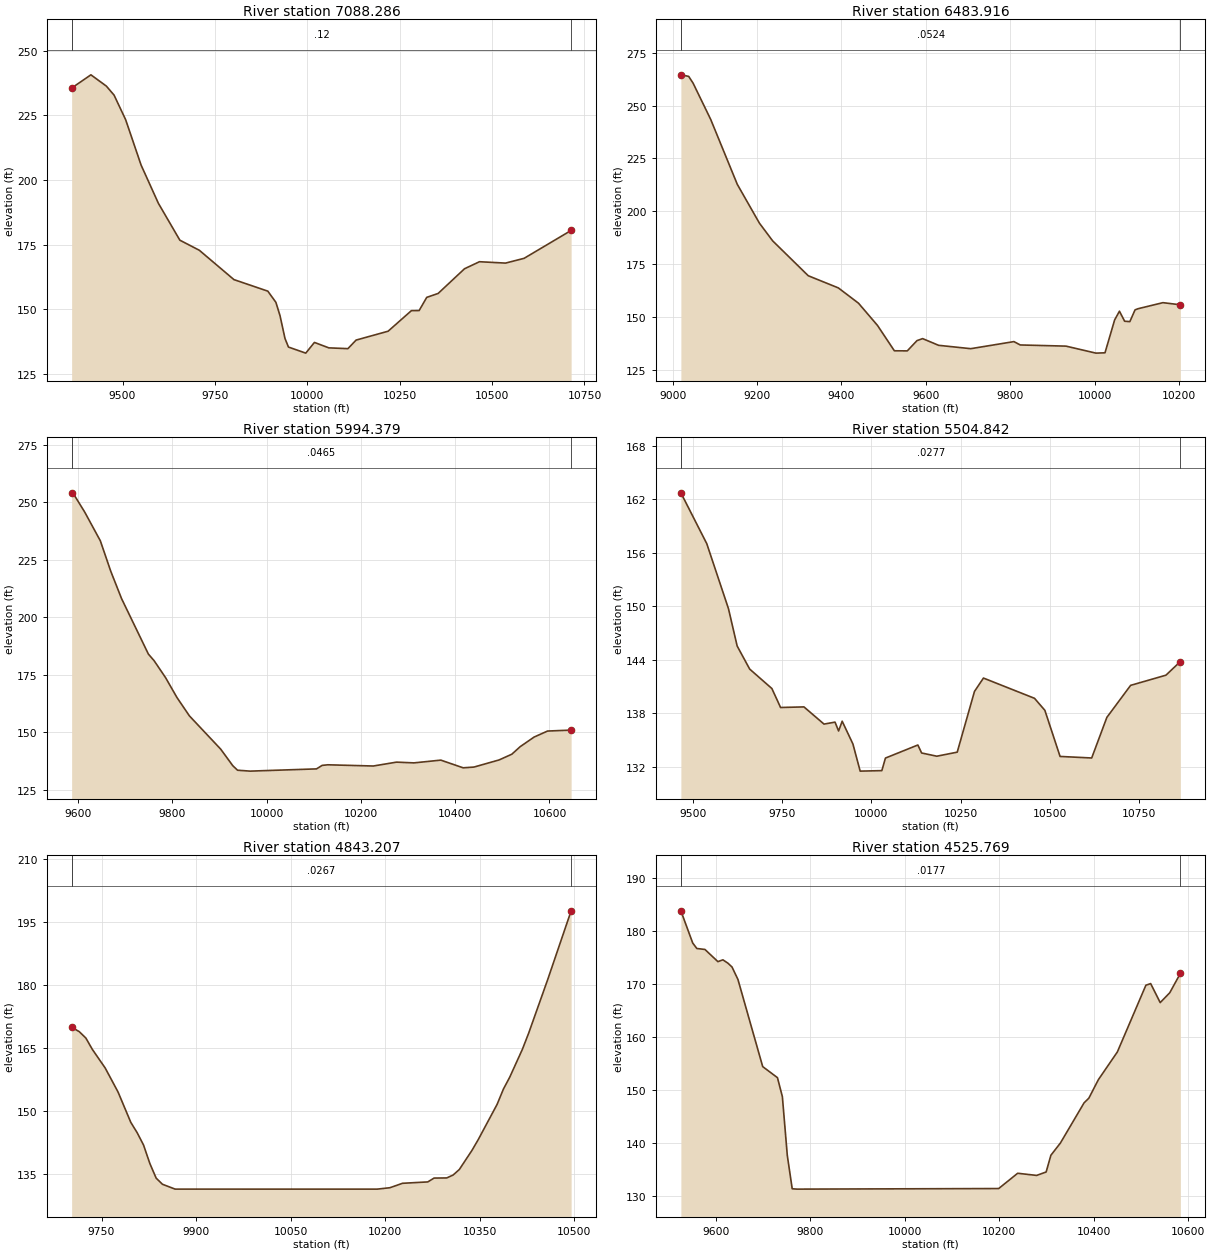
Type RM Length L Ch R = 1 ,7088.286,604.370000,604.370000,604.370000
XS GIS Cut Line= 6
795107.062306963822174.925164435795237.485140335821723.820177469
795219.639442325821651.848676043795105.721859481821442.902981708
795052.015653839821291.331644775794999.595345773820887.957977974
#Sta/Elev= 30
9362.234235.61429414.407240.73259456.177  236.379477.062232.87969508.389223.3747
9550.159205.81649596.974191.01469655.077176.73929707.674172.84519801.416161.4837
9893.142157.00989914.937152.69939926.101147.54019939.618 138.6839948.989135.3757
9995.791133.028710019.25137.171710058.21135.064210109.82134.761910132.03138.0768
10218.64141.506110281.73149.4732 10302.6149.502810323.19 154.61110353.97156.1179
10425.35165.673110465.83168.402510536.38167.871410586.63169.713210713.94180.5124
#Mann= 3 , 0 , 0
9362.234    0.12       09362.234    0.12       010713.94    0.12       0
#XS Ineff= 2 , 0
       0                               0
Bank Sta=9362.234,10713.94
Exp/Cntr=0.3,0.1

Type RM Length L Ch R = 1 ,6483.916,489.537000,489.537000,489.537000
XS GIS Cut Line= 6
795187.424127781822152.578561859795287.240972799821841.232131238
795411.724072988 821611.46890207795631.041434263821391.283904628
795755.449471498821330.539679707795863.762510409 821236.42150744
#Sta/Elev= 30
9019.502264.5172 9037.93263.79359048.404260.59639090.299243.38589153.142212.7783
9205.512194.44789236.933186.05759321.348169.55739392.652 163.8089440.346156.5898
9485.368146.08739525.385134.09229556.027 134.0449578.964138.88579592.318139.8432
 9630.29136.67069706.513135.08829808.706 138.4319823.655136.8434 9932.06136.2927
10002.94132.984410024.49 133.13610047.33 148.66710058.75152.797510071.04148.0568
10083.38147.875310095.71153.427310102.91153.975310161.75156.833810203.13155.8281
#Mann= 3 , 0 , 0
9019.502  0.0524       09019.502  0.0524       010203.13  0.0524       0
#XS Ineff= 2 , 0
       0                               0
Bank Sta=9019.502,10203.13
Exp/Cntr=0.3,0.1

Type RM Length L Ch R = 1 ,5994.379,489.536900,489.536900,489.536900
XS GIS Cut Line= 6
795303.915658612822120.185195004795377.380127452821975.097498801
795412.516144569821923.820898147795475.029996534821857.257331417
795851.868550568821602.224091061796065.862368382821410.007257575
#Sta/Elev= 30
9586.323254.19299591.989253.15229614.037245.82359647.183233.31219669.374220.0135
9692.166208.16459749.154183.97569761.276181.09959785.521173.74469809.766165.0673
9836.208157.05939902.616142.57229928.195135.37419938.237133.41729964.928133.0204
10105.68133.994510117.75135.522210129.82135.774510226.37135.248810275.42136.9334
10312.51136.6099 10369.5137.810810416.83134.465310439.73134.784910493.09  137.89
 10520.1 140.385   10538143.696810567.32147.846310595.91 150.47110645.93150.8818
#Mann= 3 , 0 , 0
9586.323  0.0465       09586.323  0.0465       010645.93  0.0465       0
#XS Ineff= 2 , 0
       0                               0
Bank Sta=9586.323,10645.93
Exp/Cntr=0.3,0.1

Type RM Length L Ch R = 1 ,5504.842,661.635900,661.635900,661.635900
XS GIS Cut Line= 6
795805.328613341822274.646276847796029.676874489821952.952206314
796023.279601306821732.150550351796065.329981208821603.108435139
796164.403863519821472.246103391796503.725427568821129.651816577
#Sta/Elev= 30
 9466.51162.69759539.041156.99839599.841149.70629624.162145.52429659.265142.9356
9721.443140.75469745.763138.63099811.297138.6955 9867.49136.76849898.283136.9896
9908.328135.99689918.336 137.0929948.476134.53359968.763131.495810029.46131.5519
 10039.5132.959510130.35134.424310140.88 133.52910183.53133.168510240.58133.6219
10288.97140.433210314.08141.929910457.04139.660310486.11138.313310528.71133.1423
10617.28 132.96910659.78137.521210726.34141.111410825.16142.251310865.71143.7809
#Mann= 3 , 0 , 0
 9466.51  0.0277       0 9466.51  0.0277       010865.71  0.0277       0
#XS Ineff= 2 , 0
       09818.754        10359.31       0
Bank Sta=9466.51,10865.71
Exp/Cntr=0.3,0.1

Type RM Length L Ch R = 1 ,4843.207,317.438000,317.438000,317.438000
XS GIS Cut Line= 6
795783.323054303822333.098773559795846.173205541822317.655307407
795955.289602765822307.642742646796065.853411216822311.039490162
796416.132849252822334.171392045796572.275792654 822327.93032599
#Sta/Elev= 30
9702.537169.97199714.723168.89759725.069167.39549735.322164.71219755.829160.2627
9776.208154.55429796.423147.35439806.529144.88879816.568141.98539826.607137.5933
9836.645134.09999846.659132.64139866.674131.495110187.42131.489510207.49131.8231
10227.55132.876410267.57133.202810277.58134.115310297.59134.148410307.59 134.819
 10317.6136.141910337.61140.672410347.61143.241310377.62151.640610387.63155.2688
10397.63158.093110417.64164.693110427.64168.541310457.65181.187710495.06197.6215
#Mann= 3 , 0 , 0
9702.537  0.0267       09702.537  0.0267       010495.06  0.0267       0
#XS Ineff= 2 , 0
       0                               0
Bank Sta=9702.537,10495.06
Exp/Cntr=0.3,0.1

Type RM Length L Ch R = 1 ,4525.769,244.768500,244.768500,244.768500
XS GIS Cut Line= 6
795632.864160569822755.451708043795765.918401777822703.397305507
795866.380487817822674.430772282 796086.86303661  822628.1694686
796254.607323691822604.546754526796667.254589295822559.545286279
#Sta/Elev= 30
9526.169183.89169551.239177.80779559.946176.7753 9577.08176.59419604.508174.2948
9615.117174.63299625.726174.0022 9634.39173.28219646.944170.93259699.402154.4592
9730.625152.36999741.032148.78229751.439137.68959761.847131.38229771.636131.3121
10198.96131.422310239.14134.307910279.32 133.90210299.42134.548610309.46137.7091
10329.55140.014510379.78147.619410389.82148.494110409.94151.984210450.19157.2299
 10510.6169.836310520.71170.142310540.91166.554110561.11168.4124 10583.6172.0743
#Mann= 3 , 0 , 0
9526.169  0.0177       09526.169  0.0177       0 10583.6  0.0177       0
#XS Ineff= 2 , 0
       0                               0
Bank Sta=9526.169,10583.6
Exp/Cntr=0.3,0.1

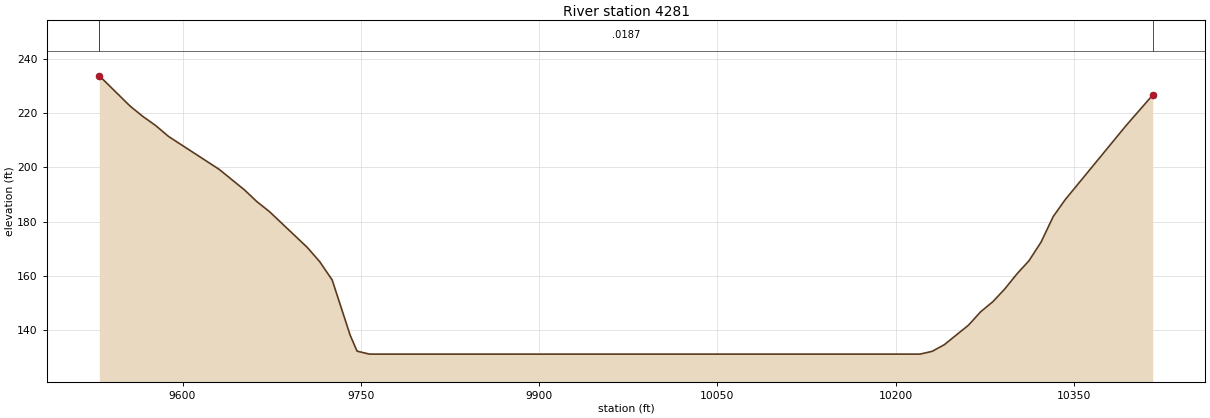
Type RM Length L Ch R = 1 ,    4281,0.000000,0.000000,0.000000
XS GIS Cut Line= 6
795690.990900281823006.519719312795755.681738312822980.230024891
795849.401009748822947.521396972796045.613891995822890.560543902
796198.099362308822853.657746123796547.184833846 822783.67071111
#Sta/Elev= 30
9530.012233.69299555.928222.54639566.722218.72529577.517215.36819588.311211.3705
9630.893199.27219652.076191.74879662.668187.3765 9673.26183.6985 9704.97170.5702
9715.447165.32289725.923158.60379741.088 138.2479746.877132.39539757.354131.3104
9767.831 131.30710220.57131.312110230.76132.333810240.95134.766910261.32141.9476
10271.51146.8597 10281.7150.543410291.89155.290210302.08160.810610312.26165.6707
10322.45 172.55210332.64181.926810342.83188.201210393.77215.303210416.37226.6337
#Mann= 3 , 0 , 0
9530.012  0.0187       09530.012  0.0187       010416.37  0.0187       0
#XS Ineff= 2 , 0
       0                               0
Bank Sta=9530.012,10416.37
Exp/Cntr=0.3,0.1